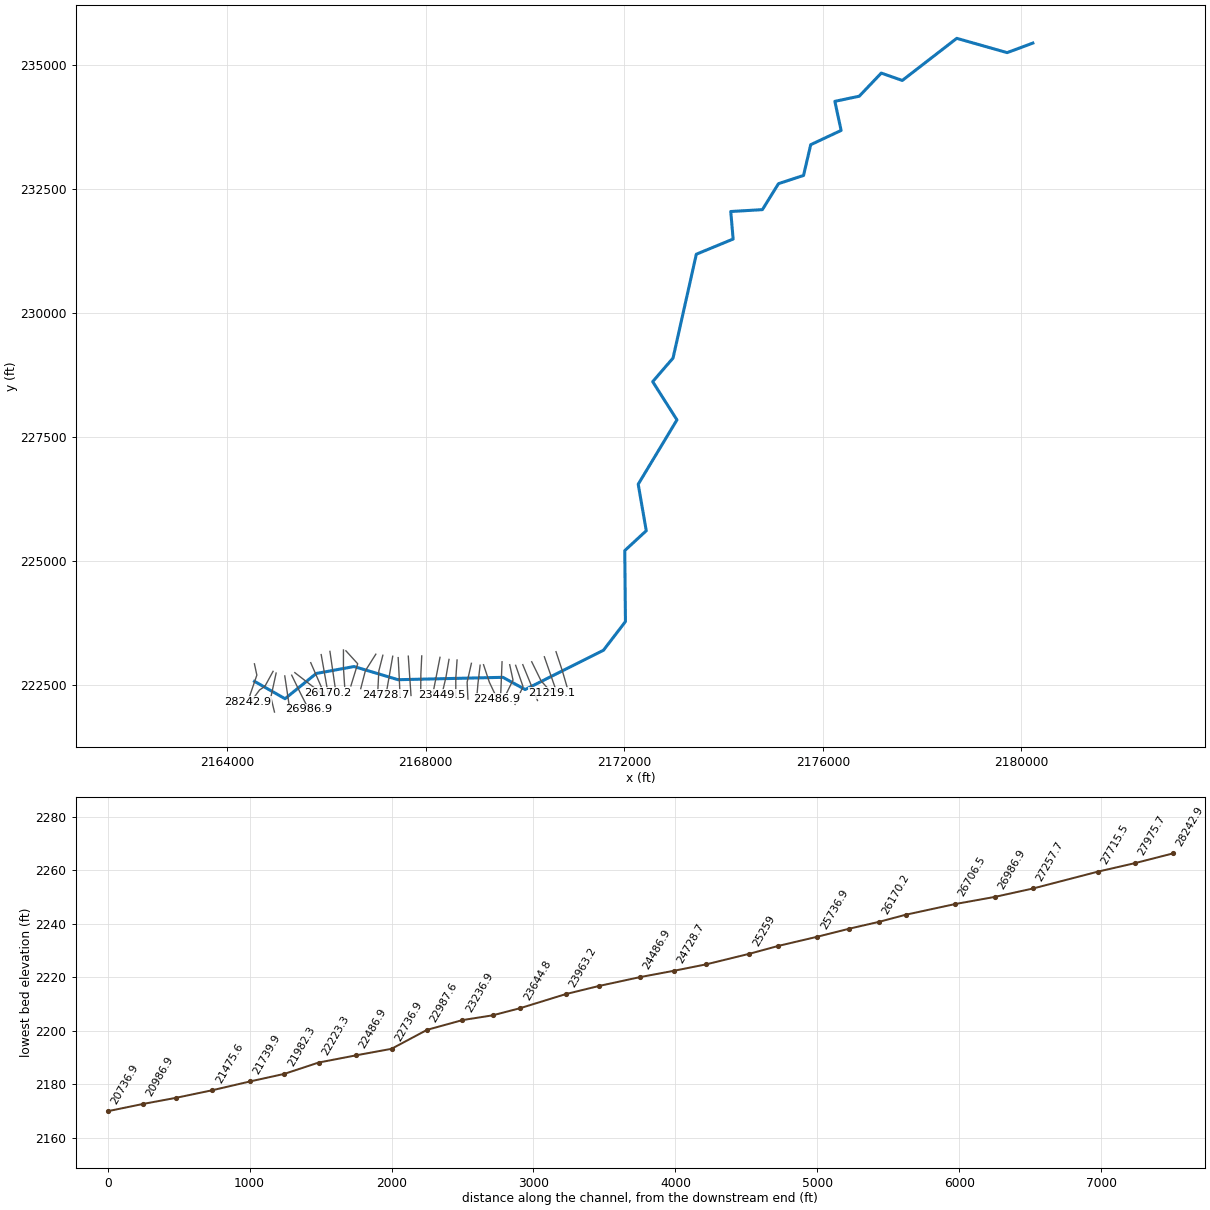
--- BACKCK2.prj (project) ---

Proj Title=BACKCK2
Current Plan=p01
Default Exp/Contr=0,0
English Units
Geom File=g01
Flow File=f01
Plan File=p01
BEGIN DESCRIPTION:
END DESCRIPTION:
DSS Export Rating Curves= 0
DSS Export Rating Curve Sorted= 0
DSS Export Volume Flow Curves= 0
DXF OffsetX= 0
DXF OffsetY= 0
DXF ScaleX= 0
DXF ScaleY= 0

--- BACKCK2.p01 (plan) ---

Plan Title=Floodplain
Program Version=4.00
Geom File=g01
Flow File=f01
K Sum by GR=0
Std Step Tol=0.01
Critical Tol=0.01
Num of Std Step Trials=20
Max Error Tol=0.3
Flow Tol Ratio=0.001
Split Flow NTrial=30
Split Flow Tol=0.02
Split Flow Ratio=0.02
Log Output Level=0
Friction Slope Method=1
Unsteady Friction Slope Method=2
Unsteady Bridges Friction Slope Method=1
Global Log Level=0
CheckData=False
Run HTab=0
Run UNet=0
Run PostProcess=0
UNET Theta=0
UNET Theta Warmup=0
UNET ZTol=0
UNET ZSATol=0
UNET MxIter=0
UNET MaxInSteps=0
UNET DtIC=0
UNET DtMin=0
UNET MaxCRTS=0
UNET WFStab=0
UNET SFStab=0
UNET WFX=0
UNET SFX=0
UNET DSS MLevel=0
UNET DZMax Abort=0
UNET Convert EG Bridges=0
UNET Use Existing IB Tables=0
UNET Froude Limit=0
UNET Froude Power=0
Write IC File=0
Echo Input=False
Echo Output=False
Write Detailed=0

--- BACKCK2.f01 (steady flow) ---

Flow Title=NFF Regression Equation
Program Version=4.10
Number of Profiles= 1
Profile Names=P100yr
River Rch & RM=BACKCK2,Main            ,28242.9
657.9741
River Rch & RM=BACKCK2,Main            ,26359.7
709.3858
River Rch & RM=BACKCK2,Main            ,25462.8
761.9025
River Rch & RM=BACKCK2,Main            ,22736.9
845.6347
River Rch & RM=BACKCK2,Main            ,19987.1
  939.31
River Rch & RM=BACKCK2,Main            ,14986.9
1037.066
River Rch & RM=BACKCK2,Main            ,11017.7
1150.948
River Rch & RM=BACKCK2,Main            ,10736.9
1283.518
River Rch & RM=BACKCK2,Main            ,9736.9
1302.281
River Rch & RM=BACKCK2,Main            ,7964.9
1441.296
River Rch & RM=BACKCK2,Main            ,438.3
1585.671
River Rch & RM=BACKCK2,Main            ,96.9
1589.426
Boundary for River Rch & Prof#=BACKCK2,Main            , 1
Up Type= 0
Dn Type= 3
Dn Slope=0.01026
DSS Import GetInterval= 0
DSS Import GetPeak= 0
DSS Import FillOption= 0

--- BACKCK2.g01 (geometry) ---

Geom Title=USGS 1m DEM
Program Version=4.10

River Reach=BACKCK2         ,Main
Reach XY= 30
     2164551.442      222581.189     2165166.025       222232.23
     2165794.497      222740.043      2166556.65        222879.8
     2167442.067      222615.043     2169554.914      222662.786
     2170002.831      222417.126     2171580.088      223207.925
     2172022.796      223785.182     2172008.907      225214.001
     2172442.067      225614.175     2172279.847      226550.048
     2173060.358      227845.696     2172571.237        228615.8
     2172981.006       229089.31     2173450.613      231181.079
     2174192.098       231486.78     2174143.967      232040.942
     2174781.384      232078.667     2175105.296      232601.609
     2175610.027      232766.817     2175754.421      233386.022
     2176367.122      233673.511     2176240.939      234258.894
      2176731.81      234362.094     2177175.821      234827.806
     2177598.998      234679.368      2178696.22      235527.458
      2179710.76      235239.568     2180229.083      235431.968

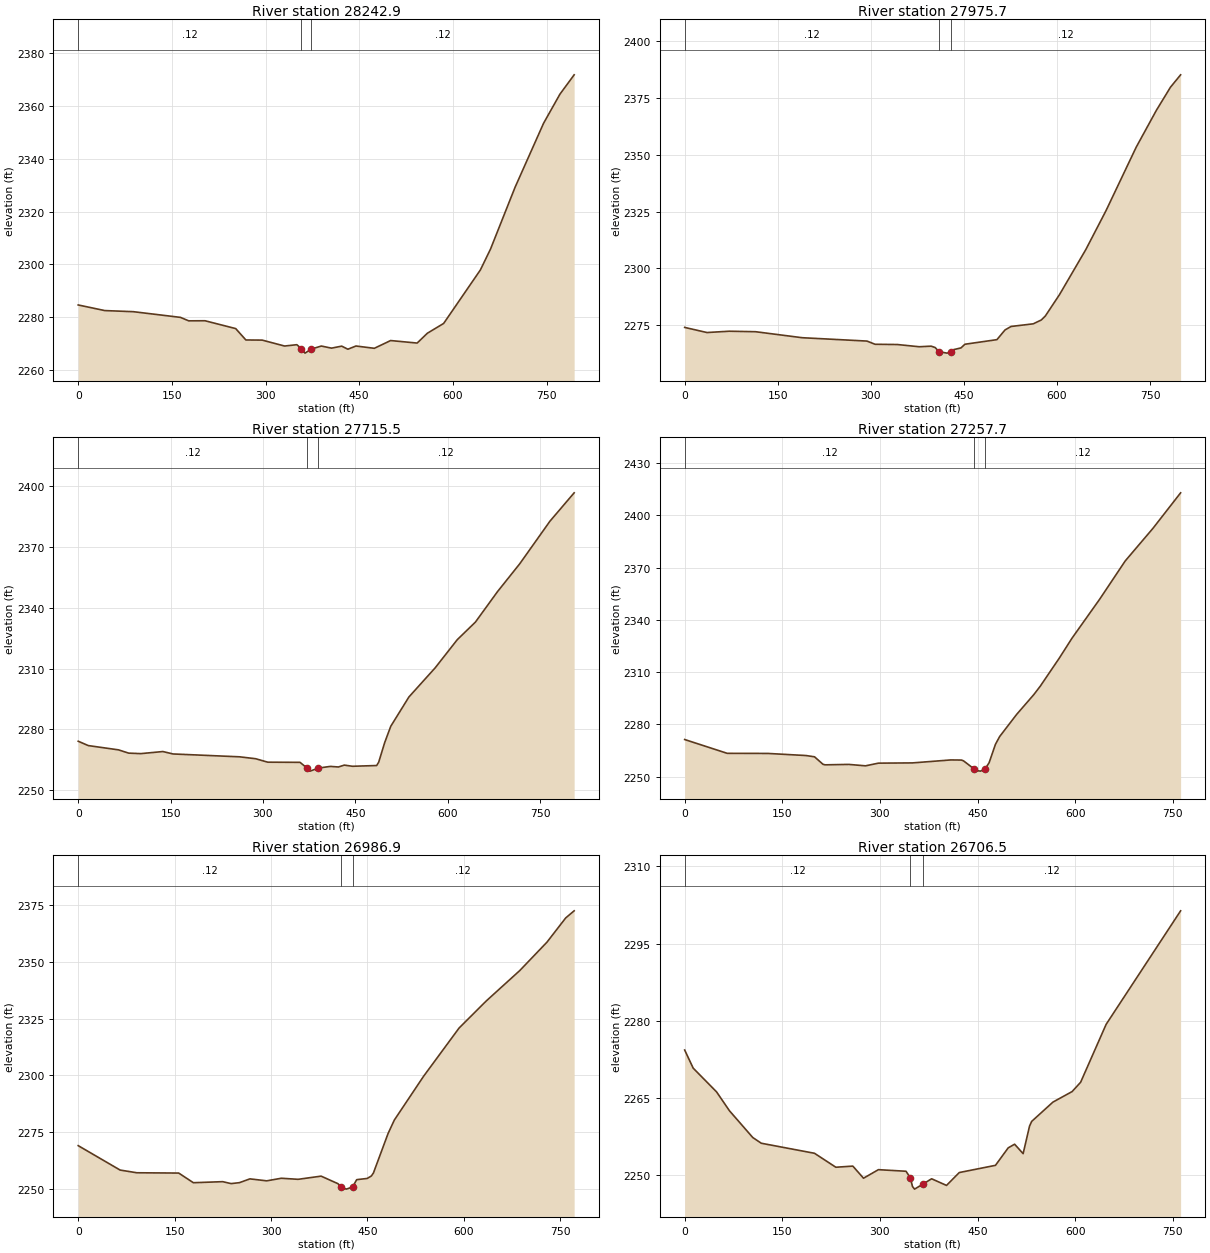
Type RM Length L Ch R = 1 ,28242.9 ,278.8,267.2,230.1
XS GIS Cut Line= 3
     2164549.777      222934.473      2164598.39      222707.032
     2164415.795      222175.909
#Sta/Elev= 30
       0 2284.57    42.6 2282.44    88.4 2282.02   163.8 2279.86   176.9 2278.55
   203.1 2278.58   252.2 2275.61   268.5 2271.29   294.6 2271.24   330.5 2268.99
   350.1  2269.5   357.4    2268   363.2  2266.3     373 2267.81   389.3 2268.99
   405.6 2268.19     422 2268.95   431.8 2267.78   444.8    2269   474.2 2268.13
   500.3 2271.07   542.8 2270.12   559.1 2273.84   585.2 2277.56     644 2297.84
   660.3 2305.79   699.5 2329.17   745.2 2353.49   771.4 2364.53   794.2 2371.88
#Mann= 3 ,-1 , 0
       0     .12       0   357.4    .045       0     373     .12       0
Bank Sta=357.4,373
XS Rating Curve= 0 ,0
Exp/Cntr=0.3,0.1

Type RM Length L Ch R = 1 ,27975.7 ,231.2,260.2,280.6
XS GIS Cut Line= 4
     2164925.333      222783.374     2164759.372      222479.666
     2164653.157      222408.303     2164459.548      222146.894
#Sta/Elev= 30
       0    2274    35.9 2271.74    71.8 2272.32   114.3  2272.1   189.4 2269.46
   293.8 2267.98   306.9 2266.57   342.8 2266.46   378.1 2265.48   397.3 2265.74
   403.7 2265.14   410.1  2263.3   422.9 2262.67   428.5 2263.34   432.5 2264.15
   445.3 2264.96   451.7 2266.58   503.3 2268.61   516.4 2272.89   526.1 2274.41
   561.9 2275.58   574.9 2277.28   581.4 2279.05   604.2 2288.45   646.5 2308.24
     679 2325.34   727.8 2353.38   760.3 2369.61   783.1 2379.83   799.4 2385.26
#Mann= 3 ,-1 , 0
       0     .12       0   410.1    .045       0   428.5     .12       0
Bank Sta=410.1,428.5
XS Rating Curve= 0 ,0
Exp/Cntr=0.3,0.1

Type RM Length L Ch R = 1 ,27715.5 ,438.2,457.7,450.4
XS GIS Cut Line= 3
     2164986.739      222748.522     2164880.524      222262.257
     2164953.546      221963.528
#Sta/Elev= 30
       0 2274.21    16.4 2272.07    65.5 2269.96    81.9 2268.36   101.5 2268.11
   137.5 2269.14   153.9 2267.95     262 2266.54   288.2  2265.6   307.8  2263.9
   360.2 2263.82   370.8  2261.2   376.6  2259.5   389.7 2260.98   409.3 2261.83
   422.4 2261.54   432.2 2262.46   445.3 2261.89   484.6 2262.25   487.9 2263.89
   497.7 2273.58   507.5 2281.56     537 2295.99   579.5 2310.28   615.5 2324.18
     645 2332.85   680.9 2347.85   716.9 2361.51     766 2382.49   805.3 2396.45
#Mann= 3 ,-1 , 0
       0     .12       0   370.8    .045       0   389.7     .12       0
Bank Sta=370.8,389.7
XS Rating Curve= 0 ,0
Exp/Cntr=0.3,0.1

Type RM Length L Ch R = 1 ,27257.7 ,259.4,270.8,282.9
XS GIS Cut Line= 2
     2165160.997      222690.436     2165273.851      221936.974
#Sta/Elev= 30
       0 2271.33    65.4  2263.4   127.5 2263.35   186.4 2262.14   199.5 2261.41
   212.5 2257.11   215.8  2256.8   251.8 2257.05   277.9 2256.23   297.6 2257.77
   349.9 2257.91   408.7 2259.61   425.1 2259.55   428.4 2259.09   444.7 2254.42
     448 2253.51   454.5 2253.19   461.3 2254.41   467.6 2257.92   477.4 2268.55
   483.9 2273.05   510.1  2285.8   536.2 2297.04   546.1 2301.86   575.5 2318.06
   595.1 2329.54   637.6 2351.92   676.8 2373.86   719.4 2392.58   761.9 2412.97
#Mann= 3 ,-1 , 0
       0     .12       0   444.7    .045       0   461.3     .12       0
Bank Sta=444.7,461.3
XS Rating Curve= 0 ,0
Exp/Cntr=0.3,0.1

Type RM Length L Ch R = 1 ,26986.9 ,262.3,280.4,329.9
XS GIS Cut Line= 3
       2165300.3      222705.864     2165482.458      222330.589
     2165644.307      222015.072
#Sta/Elev= 30
       0 2269.13    65.2  2258.4    91.2 2257.21   156.4 2257.08   179.2 2252.84
   224.9  2253.3   237.9 2252.45   250.9 2252.86   267.2 2254.53   293.3 2253.66
   316.1  2254.8   342.2 2254.33     378 2255.73   404.1 2252.43   409.6 2250.96
   417.2 2250.02   426.9 2250.94   433.4 2254.18   449.7 2254.71   456.2 2255.79
   459.4  2257.1   482.2 2274.45     492  2280.4   537.5 2299.63   592.8 2320.85
   635.1 2332.75   687.2 2346.09   729.5 2358.57   758.7 2369.23   771.8 2372.34
#Mann= 3 ,-1 , 0
       0     .12       0   409.6    .045       0   426.9     .12       0
Bank Sta=409.6,426.9
XS Rating Curve= 0 ,0
Exp/Cntr=0.3,0.1

Type RM Length L Ch R = 1 ,26706.5 ,357.7,346.8,285.9
XS GIS Cut Line= 2
      2165363.47      222756.821     2165965.907      222290.471
#Sta/Elev= 30
       0 2274.35    13.1 2270.83      49 2266.22    68.7 2262.57   104.6 2257.36
   117.7 2256.25   199.4  2254.3   232.2 2251.59   258.3 2251.81   274.7 2249.46
   297.6 2251.12     340 2250.81   346.7 2249.52   349.9 2247.86   353.1 2247.34
   366.2 2248.33   379.3 2249.35   402.2 2248.06   421.8 2250.56   477.4 2251.96
     497 2255.36   506.8 2256.06   519.9 2254.23   529.7 2259.56     533 2260.49
   565.7 2264.24   595.1 2266.28   608.2 2268.09   647.4 2279.34   761.8 2301.38
#Mann= 3 ,-1 , 0
       0     .12       0   346.7    .045       0   366.2     .12       0
Bank Sta=346.7,366.2
XS Rating Curve= 0 ,0
Exp/Cntr=0.3,0.1

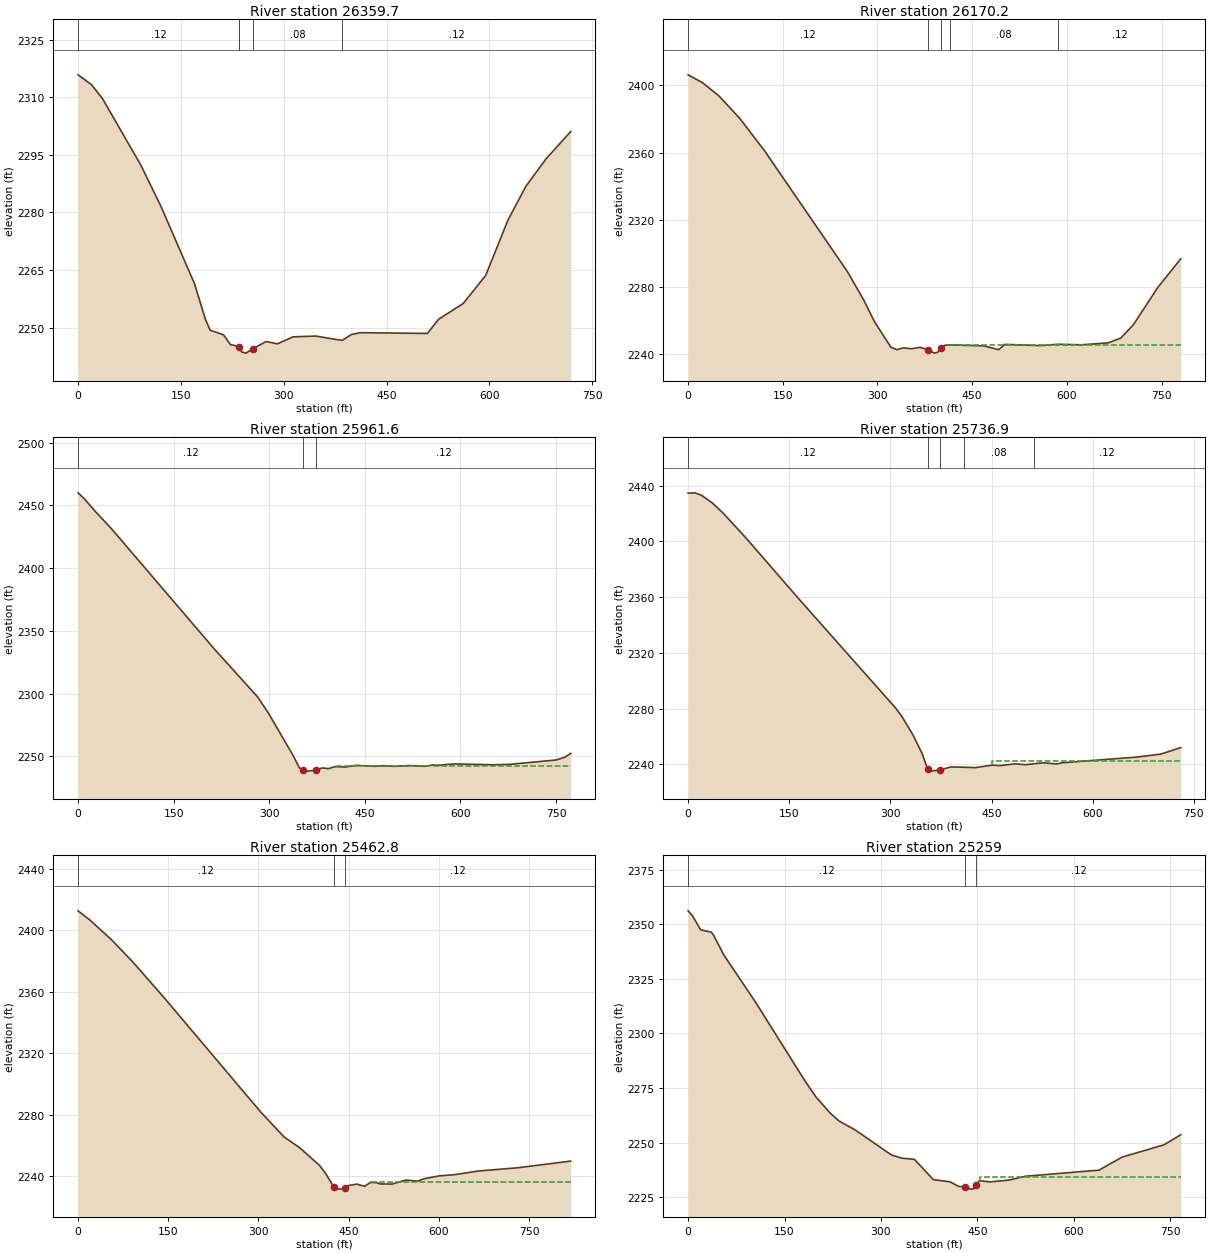
Type RM Length L Ch R = 1 ,26359.7 ,198,189.5,180.1
XS GIS Cut Line= 2
     2165683.774      222957.633     2165970.886      222298.769
#Sta/Elev= 30
       0 2315.85    19.6 2313.29    35.9 2309.58    91.5 2292.35   120.9 2281.61
   169.9 2261.42   186.2 2251.94   192.7 2249.32   212.3 2248.12   222.1  2245.6
  234.612245.056   235.2 2244.94   238.5 2243.67     245 2243.35   254.8 2244.49
   274.4 2246.36   290.8 2245.77   313.6 2247.59   346.3  2247.8  385.252246.657
   398.6 2248.18   411.6 2248.68   509.6 2248.48     526 2252.18   561.9 2256.29
   594.6 2263.57   627.2 2278.04   653.4 2286.85   682.8 2293.99   718.7 2301.08
#Mann= 5 ,-1 , 0
       0     .12       0  234.61     .08       0   235.2    .045       0
   254.8     .08       0  385.25     .12       0
Bank Sta=235.2,254.8
XS Rating Curve= 0 ,0
Exp/Cntr=0.3,0.1

Type RM Length L Ch R = 1 ,26170.2 ,210.1,208.6,200.1
XS GIS Cut Line= 2
     2165894.544      223120.275     2166030.632      222351.876
#Sta/Elev= 30
       0 2406.23      23 2401.53    49.2 2393.56      82 2380.25   121.3 2360.94
   252.5 2289.11   278.7 2271.92   295.1 2259.48   321.3  2244.2   331.2 2242.71
     341 2243.84   354.1 2243.28   367.2 2244.13   380.3 2242.71   390.2 2240.68
   396.7 2241.44   399.9 2243.65   406.6 2245.36  415.212245.574   468.9 2244.98
   491.8 2242.71   501.7 2245.89   557.4 2245.14     5862245.961     623 2245.63
   665.6 2246.79   685.3 2249.62   704.9 2257.35   744.3 2279.89   780.4 2296.81
#Mann= 5 ,-1 , 0
       0     .12       0   380.3    .045       0   399.9     .12       0
  415.21     .08       0     586     .12       0
#XS Ineff= 2 , 0
                          413.77          2245.6
Permanent Ineff=
       F       F
Bank Sta=380.3,399.9
XS Rating Curve= 0 ,0
Exp/Cntr=0.3,0.1

Type RM Length L Ch R = 1 ,25961.6 ,230,224.8,221.5
XS GIS Cut Line= 2
     2166070.462      223184.999     2166181.656       222419.92
#Sta/Elev= 30
       0 2460.08     9.8 2455.41    26.2 2445.73    52.4 2431.48   212.9 2336.08
   281.7 2297.35   298.1 2284.94   337.4 2250.68   347.2 2240.89   353.7 2238.72
   360.4 2238.13   373.4 2238.87   383.3 2240.67   393.1 2240.13   402.9 2241.71
   419.3 2241.38   435.7 2242.73   465.2 2242.02   478.3 2242.41   497.9 2241.93
   520.9 2242.58   543.8    2242   556.9 2243.04   566.7 2242.82   589.7 2243.89
   651.9 2243.19   678.1 2243.54   750.2 2247.03   763.3 2249.11   773.1  2252.3
#Mann= 3 ,-1 , 0
       0     .12       0   353.7    .045       0   373.4     .12       0
#XS Ineff= 2 , 0
                          406.78         2241.84
Permanent Ineff=
       F       F
Bank Sta=353.7,373.4
XS Rating Curve= 0 ,0
Exp/Cntr=0.3,0.1

Type RM Length L Ch R = 1 ,25736.9 ,285.1,274.1,259.6
XS GIS Cut Line= 3
     2166342.693      223213.718     2166342.693      222850.286
     2166367.397      222483.899
#Sta/Elev= 30
       0 2434.66     9.8 2434.92    19.6 2433.24      36 2427.63    52.4 2420.12
    85.1 2402.92   163.7 2359.07   307.8  2280.4   317.6 2273.94     334 2260.67
   347.1 2247.64   353.6 2238.82   355.9 2236.75   356.9 2235.85   360.2 2235.12
   373.3 2235.91   389.7 2238.16   409.72237.899   425.7 2237.63     452 2239.45
   461.8 2239.04   484.8 2240.35   501.1 2239.73  512.832240.434   527.4  2241.1
     547 2240.21   553.6 2241.05   665.1 2245.19   701.1 2247.36   730.6 2251.98
#Mann= 5 ,-1 , 0
       0     .12       0   355.9    .045       0   373.3     .12       0
   409.7     .08       0  512.83     .12       0
#XS Ineff= 2 , 0
                          450.95         2242.41
Permanent Ineff=
       F       F
Bank Sta=355.9,373.3
XS Rating Curve= 0 ,0
Exp/Cntr=0.3,0.1

Type RM Length L Ch R = 1 ,25462.8 ,201.3,203.7,205.3
XS GIS Cut Line= 3
     2166392.426      223196.617      2166629.75      222936.058
     2166492.415      222490.011
#Sta/Elev= 30
       0 2412.72    19.6 2406.78    55.5 2393.95    91.4 2379.32   143.6 2355.98
   303.5 2281.97   342.6  2265.6   368.8 2258.55   401.4 2247.16   411.2 2242.19
   424.9 2233.34   427.5 2232.06   430.8  2231.7   440.6 2231.88   443.8 2232.62
   450.4  2234.1   463.4 2234.96   476.5 2233.55   486.2 2236.05     496 2235.88
   502.6 2235.05   522.2 2234.99     545 2237.62   564.6 2236.87   574.4 2238.38
   600.5 2240.31   626.6 2241.13   665.8 2243.49     731 2245.59   819.2 2249.93
#Mann= 3 ,-1 , 0
       0     .12       0   424.9    .045       0   443.8     .12       0
#XS Ineff= 2 , 0
                          486.56         2236.08
Permanent Ineff=
       F       F
Bank Sta=424.9,443.8
XS Rating Curve= 0 ,0
Exp/Cntr=0.3,0.1

Type RM Length L Ch R = 1 ,25259   ,298.6,304.5,310.2
XS GIS Cut Line= 3
     2166994.864      223128.573     2166784.094      222794.992
     2166691.156      222434.857
#Sta/Elev= 30
       0 2356.15     6.5 2354.03    19.6 2347.45    35.9 2346.41    39.1 2345.32
    55.4 2336.04   104.4 2314.58   182.6 2277.95   198.9 2270.95   221.8 2263.34
   234.8 2259.97   260.9 2255.68   316.3  2244.4   332.6 2242.94   352.2 2242.38
   381.5 2233.12   407.6  2232.1   420.7 2230.02   430.5 2229.79   440.3 2228.76
   443.5 2228.82   448.3 2230.59   453.3 2232.62   469.6 2232.07     499 2232.89
   525.1 2234.67   639.3 2237.44   675.2 2243.43   740.4 2249.04   766.5 2253.68
#Mann= 3 ,-1 , 0
       0     .12       0   430.5    .045       0   448.3     .12       0
#XS Ineff= 2 , 0
                          453.86         2234.38
Permanent Ineff=
       F       F
Bank Sta=430.5,448.3
XS Rating Curve= 0 ,0
Exp/Cntr=0.3,0.1

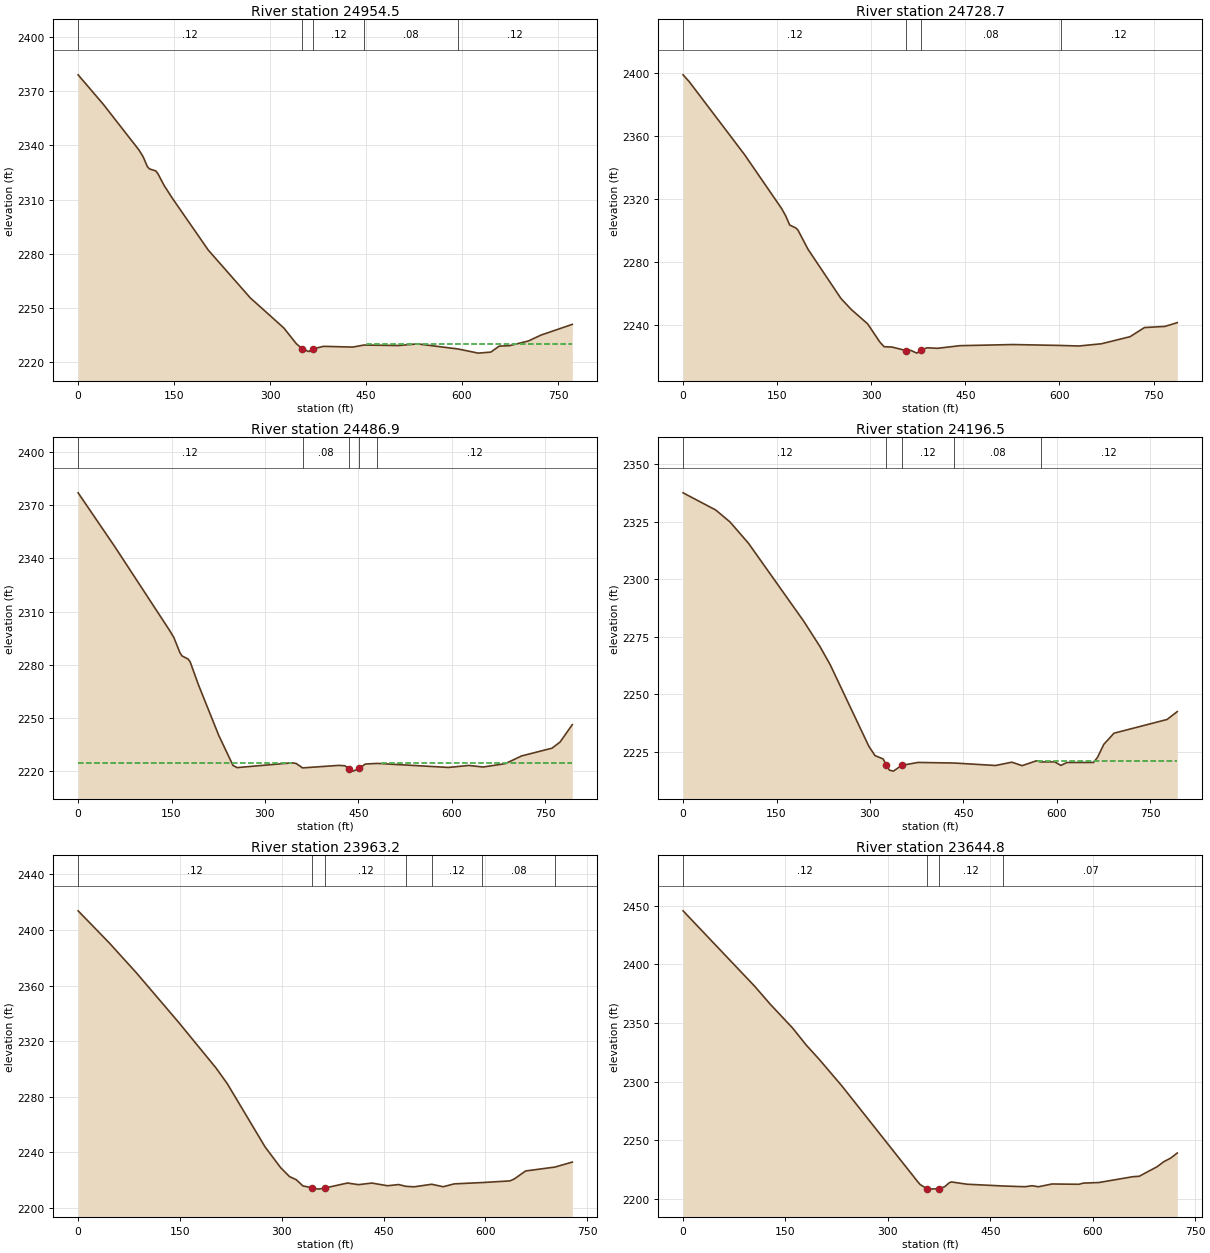
Type RM Length L Ch R = 1 ,24954.5 ,227.9,225.8,221.8
XS GIS Cut Line= 3
     2167136.356      223107.489     2167056.061      222792.819
      2167032.19      222345.771
#Sta/Elev= 30
       0 2379.18    39.4 2362.82    95.1 2337.49   101.7 2333.67   108.2 2328.32
   111.5    2327   121.4 2325.89   124.6 2324.41   134.5 2317.78   147.6 2310.56
   203.4 2281.98     269 2255.49   321.5 2238.76   341.1 2230.01   349.8 2227.36
   360.7 2225.65   367.2 2227.18   383.6 2228.57   429.3 2228.16  446.642229.286
   501.2 2229.02   530.6 2229.91  593.972227.098   625.4  2224.8     645 2225.37
   658.1 2228.68   674.4 2228.94   703.8 2231.54   723.4  2234.8   772.4 2240.75
#Mann= 5 ,-1 , 0
       0     .12       0   349.8    .045       0   367.2     .12       0
  446.64     .08       0  593.97     .12       0
#XS Ineff= 2 , 0
                          452.28          2229.6
Permanent Ineff=
       F       F
Bank Sta=349.8,367.2
XS Rating Curve= 0 ,0
Exp/Cntr=0.3,0.1

Type RM Length L Ch R = 1 ,24728.7 ,231.4,241.8,249.8
XS GIS Cut Line= 2
     2167335.083      223087.082      2167199.29      222311.048
#Sta/Elev= 30
       0  2399.1     9.8 2394.76    98.1 2348.38   156.9 2314.32   163.4 2309.74
     170 2303.72   179.8 2301.86   183.1 2300.56   199.4 2288.19   251.7  2257.1
   268.1 2250.14   294.2    2241   313.8 2229.39   320.4 2226.51   333.4 2226.25
   355.7    2224   362.9 2224.17   372.7 2222.41   379.2 2224.31     389 2225.82
   405.4 2225.46   441.3 2227.14   526.3 2227.86  601.762227.283   630.9 2226.93
   666.9 2228.35   712.6 2232.85   735.5 2238.65   768.2 2239.38   787.8 2241.76
#Mann= 4 ,-1 , 0
       0     .12       0   355.7    .045       0   379.2     .08       0
  601.76     .12       0
Bank Sta=355.7,379.2
XS Rating Curve= 0 ,0
Exp/Cntr=0.3,0.1

Type RM Length L Ch R = 1 ,24486.9 ,287.6,290.4,289.7
XS GIS Cut Line= 3
     2167445.261      223059.613     2167468.283      222618.515
     2167484.169      222267.024
#Sta/Elev= 30
       0 2376.97    58.9 2346.61   147.2 2299.21   153.8 2295.33   163.6 2286.74
   166.9 2284.97   176.7 2283.22     180 2281.57     193 2268.92   225.8  2240.2
   248.7 2223.24   255.2    2222   343.5 2224.69   350.1 2224.34   360.42221.838
   418.8 2223.25   428.6 2223.04   434.2 2221.39   441.7 2220.01   451.5 2221.58
   461.2 2224.01  480.572224.362   594.8 2222.09   627.4 2223.22   650.2 2222.33
     686 2224.22   712.1 2228.57     761 2232.95     774 2236.43   793.6 2246.25
#Mann= 5 ,-1 , 0
       0     .12       0   360.4     .08       0   434.2    .045       0
   451.5     .08       0  480.57     .12       0
#XS Ineff= 2 , 0
          343.53  2224.7  487.74         2224.53
Permanent Ineff=
       F       F
Bank Sta=434.2,451.5
XS Rating Curve= 0 ,0
Exp/Cntr=0.3,0.1

Type RM Length L Ch R = 1 ,24196.5 ,237.6,233.3,229.9
XS GIS Cut Line= 2
     2167648.749      223088.742     2167703.516      222297.109
#Sta/Elev= 30
       0 2337.66    52.5 2330.18    75.4 2324.98   104.9 2315.78   193.5 2281.94
   219.7 2270.89   236.1    2263   298.4 2227.43   308.2 2223.43   321.3 2221.96
   326.2 2219.43   331.2 2217.11   337.7 2216.68   350.9 2219.17   377.1 2220.46
  435.562220.198   501.7 2219.13   527.9 2220.57   544.3 2219.06   567.3 2221.16
   574.42220.691   596.8  2220.7   606.6 2219.17   616.5 2220.44   659.1 2220.45
   665.6 2222.73   675.5  2228.3   691.9 2233.17   777.1 2239.13   793.5 2242.55
#Mann= 5 ,-1 , 0
       0     .12       0   326.2    .045       0   350.9     .12       0
  435.56     .08       0   574.4     .12       0
#XS Ineff= 2 , 0
                          568.65         2221.18
Permanent Ineff=
       F       F
Bank Sta=326.2,350.9
XS Rating Curve= 0 ,0
Exp/Cntr=0.3,0.1

Type RM Length L Ch R = 1 ,23963.2 ,323.4,318.4,311.4
XS GIS Cut Line= 3
     2167919.805      223093.951     2167902.308      222730.372
     2167899.167      222366.221
#Sta/Elev= 30
       0 2413.84    45.9 2390.76    85.3 2369.55   147.6 2333.93   203.3 2300.74
   219.7 2289.57   275.5 2244.02   298.4 2229.11   311.5 2222.66   321.4 2220.43
   331.2 2215.96   344.3 2214.66   354.2 2213.64     364 2214.48   396.8 2218.02
   413.2 2216.86   432.9    2218   455.9 2216.07   472.3 2216.92  482.852215.659
   495.2 2215.31  520.932217.142   537.9 2215.37   554.3 2217.43  595.592218.369
   636.3 2219.55   642.9    2221   659.3 2226.69  702.752229.521   728.2  2233.1
#Mann= 7 ,-1 , 0
       0     .12       0   344.3    .045       0     364     .12       0
  482.85     .08       0  520.93     .12       0  595.59     .08       0
  702.75     .12       0
Bank Sta=344.3,364
XS Rating Curve= 0 ,0
Exp/Cntr=0.3,0.1

Type RM Length L Ch R = 1 ,23644.8 ,194.3,195.3,193.9
XS GIS Cut Line= 2
     2168287.698      223065.508     2168148.291      222355.195
#Sta/Elev= 30
       0 2445.75   104.8 2381.48   127.7  2366.1   160.5 2345.76   180.2 2331.41
   199.8 2318.84   232.6 2296.45   343.9 2214.62   347.2 2212.36     357  2208.9
   360.3 2208.42   374.7 2208.79   383.2 2210.46   389.8 2213.81     393 2214.56
     416  2212.6  469.182211.087   501.1 2210.47     511 2211.31   520.8 2210.46
   540.4  2212.8   579.8 2212.56   586.3 2213.55   609.2 2214.05   658.4 2218.98
   668.2  2219.4   694.4 2227.53   704.2 2231.84     714 2234.77   723.9 2239.23
#Mann= 4 ,-1 , 0
       0     .12       0     357    .045       0   374.7     .12       0
  469.18     .07       0
Bank Sta=357,374.7
XS Rating Curve= 0 ,0
Exp/Cntr=0.3,0.1

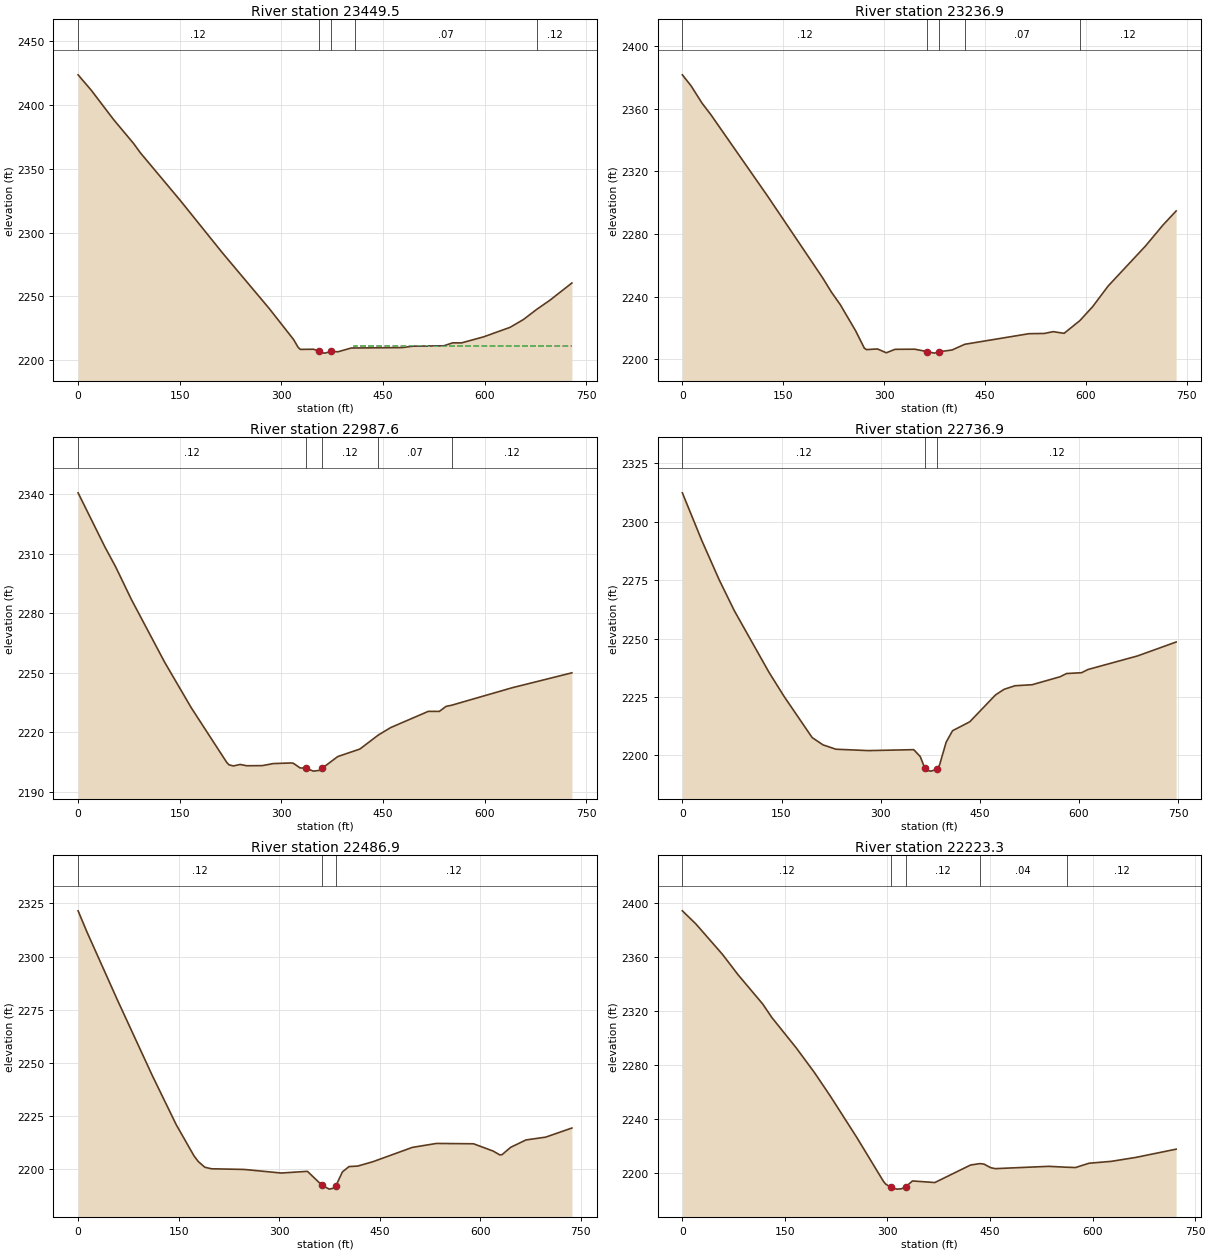
Type RM Length L Ch R = 1 ,23449.5 ,208,212.6,220.4
XS GIS Cut Line= 3
     2168468.857      223023.551     2168407.222      222664.948
     2168324.449      222309.673
#Sta/Elev= 30
       0 2423.31    19.7 2411.07    52.4  2388.3      82 2369.55    91.8  2362.4
   150.8 2325.06   213.1 2284.03   281.9 2240.67     318 2216.32   324.5 2210.37
   327.8 2208.64   347.5 2208.76   354.8 2207.25   357.3  2206.3   363.9 2205.72
   373.6 2207.03   383.4 2206.78     403 2209.71  408.81 2209.75   477.9 2210.04
   494.1 2211.14   539.7 2211.46   552.8 2213.77   565.8 2213.72   598.4 2218.46
   637.4 2225.88     657 2231.96  677.092240.082   696.1 2247.05   728.6 2260.55
#Mann= 5 ,-1 , 0
       0     .12       0   354.8    .045       0   373.6     .12       0
  408.81     .07       0  677.09     .12       0
#XS Ineff= 2 , 0
                          407.33         2210.91
Permanent Ineff=
       F       F
Bank Sta=354.8,373.6
XS Rating Curve= 0 ,0
Exp/Cntr=0.3,0.1

Type RM Length L Ch R = 1 ,23236.9 ,254.1,249.3,239
XS GIS Cut Line= 3
     2168631.246      223011.898     2168605.636      222641.085
     2168605.636      222278.443
#Sta/Elev= 30
       0 2381.57      13 2374.51    29.3 2363.48    42.4 2356.13   127.2 2303.89
   208.7 2251.94   221.7 2242.87   234.8  2234.9   257.6 2218.24   270.6 2207.13
   273.9 2206.19   290.2  2206.6   303.2 2204.16   316.3 2206.37   345.6 2206.45
   364.2 2204.88     375 2203.94   381.5 2204.78   401.1 2205.95  419.972209.578
   515.4 2216.35   538.3 2216.49   551.4 2217.65   567.7 2216.58     5912224.652
   610.2 2233.64   633.1 2246.74   688.6 2272.26   714.7 2285.69   734.3 2294.71
#Mann= 5 ,-1 , 0
       0     .12       0   364.2    .045       0   381.5     .12       0
  419.97     .07       0     591     .12       0
Bank Sta=364.2,381.5
XS Rating Curve= 0 ,0
Exp/Cntr=0.3,0.1

Type RM Length L Ch R = 1 ,22987.6 ,245.2,250.7,256.3
XS GIS Cut Line= 3
     2168920.009      222944.356     2168833.709      222564.306
     2168850.305      222225.746
#Sta/Elev= 30
       0 2340.63    39.3 2313.52    55.7 2303.11    78.6 2286.89   127.7 2255.22
     167 2232.24   219.4 2204.66   222.7 2203.46   229.2 2202.92   239.1 2203.66
   248.9    2203   271.8 2203.07   288.2  2204.1   314.4 2204.41   317.7 2204.24
   327.5 2201.93   335.9 2201.78   347.2 2200.29     357  2200.7   360.2 2201.75
   383.2 2207.64   415.8 2211.42  443.062218.493   461.4 2222.27   516.8 2230.43
   533.1 2230.41   542.9 2232.92  551.382233.536   640.7 2242.35   728.7 2249.86
#Mann= 5 ,-1 , 0
       0     .12       0   335.9    .045       0   360.2     .12       0
  443.06     .07       0  551.38     .12       0
Bank Sta=335.9,360.2
XS Rating Curve= 0 ,0
Exp/Cntr=0.3,0.1

Type RM Length L Ch R = 1 ,22736.9 ,233.4,250,270
XS GIS Cut Line= 3
       2169095.8      222907.173     2169051.607      222533.595
      2169020.17      222164.196
#Sta/Elev= 30
       0 2312.43    29.4 2292.01    55.6 2275.23    78.5 2261.98   130.8 2235.65
   153.7 2225.27   196.3 2207.58   212.6 2204.46   232.2 2202.58   281.3 2201.98
     350 2202.39   359.8 2199.43   366.4 2194.72   369.6 2193.48   376.2 2193.19
   385.9  2194.1   389.2 2195.99     399 2205.59   408.7 2210.51   434.7 2214.32
   473.7 2225.85   486.8 2228.26     503 2229.77     529 2230.21   571.3 2233.62
   581.1 2235.01   603.8 2235.35   613.6 2236.74   688.4 2242.54   746.9 2248.51
#Mann= 3 ,-1 , 0
       0     .12       0   366.4    .045       0   385.9     .12       0
Bank Sta=366.4,385.9
XS Rating Curve= 0 ,0
Exp/Cntr=0.3,0.1

Type RM Length L Ch R = 1 ,22486.9 ,277,263.6,244.3
XS GIS Cut Line= 3
     2169164.553      222916.287       2169282.1       222563.69
     2169438.776      222233.613
#Sta/Elev= 30
       0 2321.51      13 2311.73    58.7  2279.6   110.8 2244.08   146.7 2220.88
   172.8 2206.48   179.3 2203.73   189.1 2201.04   198.9 2200.31   247.8    2200
   303.2 2198.32   342.3 2199.11   364.2 2192.51   374.9 2190.75   381.5 2191.22
   384.7 2192.26   394.5 2198.84   404.3 2201.34   417.4 2201.59   440.2 2203.65
   498.9 2210.36   534.8 2212.22   590.2 2212.06   619.6 2208.62   629.4 2206.83
   632.7 2206.93   645.7 2210.41   668.5 2213.86   697.9 2215.18     737 2219.46
#Mann= 3 ,-1 , 0
       0     .12       0   364.2    .045       0   384.7     .12       0
Bank Sta=364.2,384.7
XS Rating Curve= 0 ,0
Exp/Cntr=0.3,0.1

Type RM Length L Ch R = 1 ,22223.3 ,256.1,241,226.1
XS GIS Cut Line= 2
     2169537.383      222975.889     2169508.044      222254.186
#Sta/Elev= 30
       0 2394.17    19.6 2384.57    58.8 2361.85    81.7  2346.7   117.7 2325.06
   130.7 2315.29   166.7 2292.57   192.8 2274.69   215.7 2257.54   254.9 2226.55
   294.2 2193.77   297.4  2191.8     305 2189.38   313.8 2188.05   320.3 2188.28
   326.8 2189.82   336.6  2194.1   369.3 2192.93   421.6 2205.91  435.142206.943
   441.2 2206.59     451 2203.95   457.6 2203.22     536 2204.93  562.082204.263
   575.2 2204.06   594.8 2207.22   627.5 2208.63   663.5 2211.56   722.3 2217.64
#Mann= 5 ,-1 , 0
       0     .12       0     305    .045       0   326.8     .12       0
  435.14     .04       0  562.08     .12       0
Bank Sta=305,326.8
XS Rating Curve= 0 ,0
Exp/Cntr=0.3,0.1

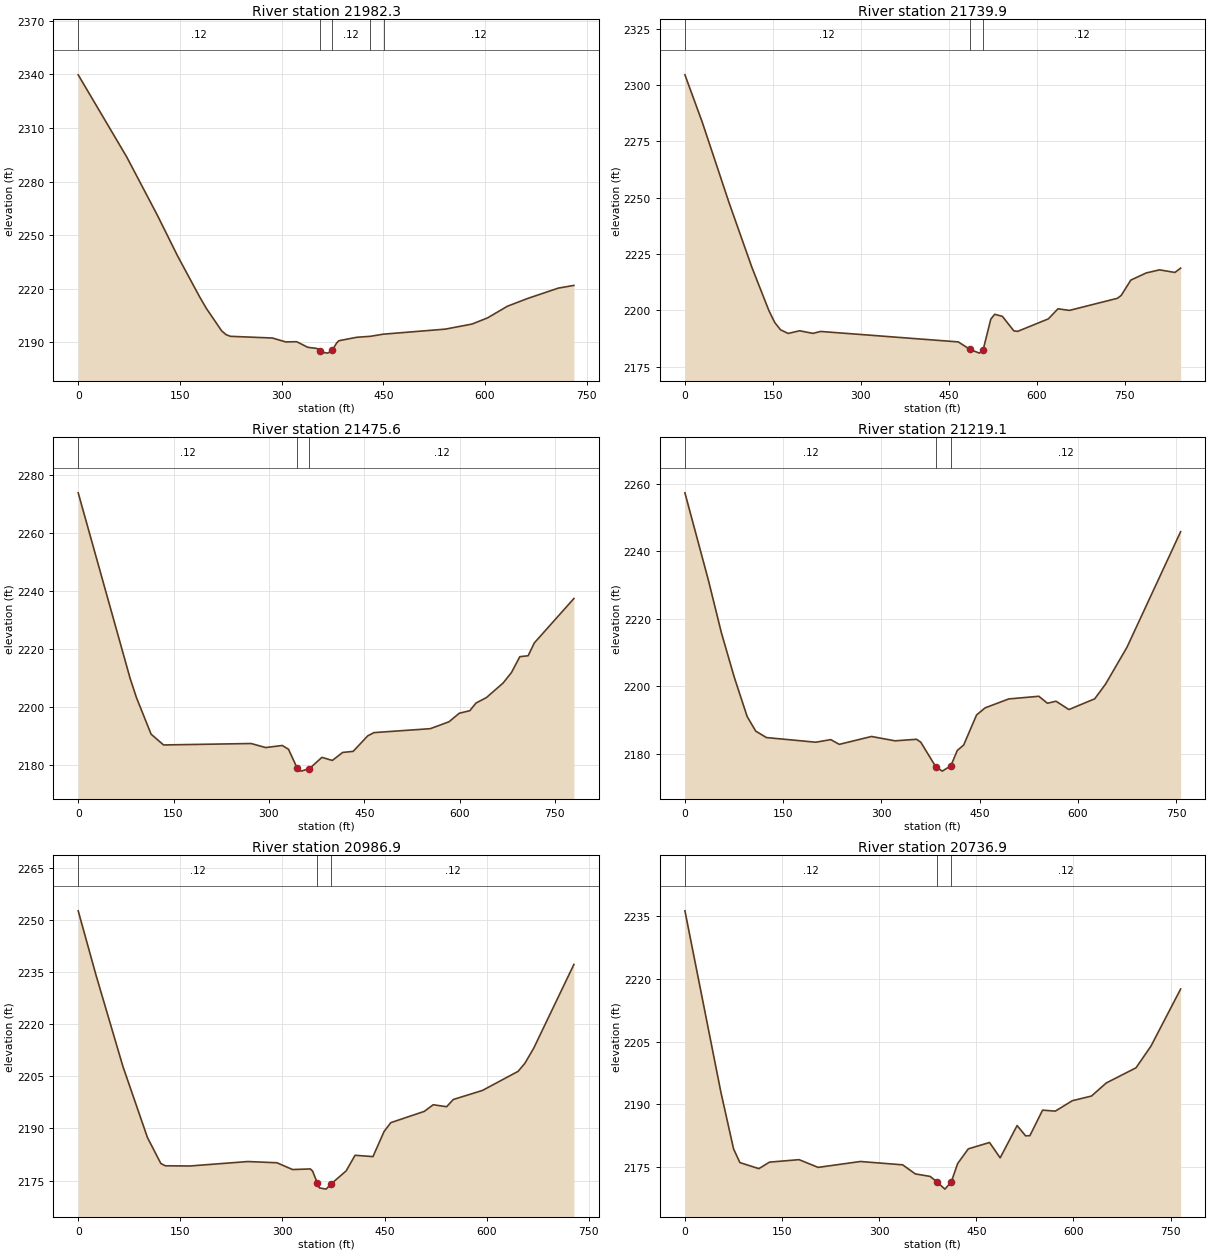
Type RM Length L Ch R = 1 ,21982.3 ,240.5,242.4,243.7
XS GIS Cut Line= 3
     2169691.726      222916.143     2169758.111      222607.456
     2169574.931      222234.637
#Sta/Elev= 30
       0 2339.81    71.6 2293.76   117.2 2260.79   146.5 2238.35     179 2215.44
   188.8 2209.02   211.6 2196.29   218.1 2194.18   224.6 2193.24   286.4 2192.29
     306 2190.11   322.3 2190.22   338.6 2187.08   351.7 2186.46   357.2 2185.21
   361.5 2184.21   368.1 2183.82   374.6 2185.35   381.2 2189.51   384.4 2190.76
   410.6 2192.69     4312193.251  450.322194.454   541.4 2197.27   580.7  2200.1
   603.6 2203.54     633  2210.1   662.4 2214.39   708.2 2220.27   731.1 2221.78
#Mann= 5 ,-1 , 0
       0     .12       0   357.2    .045       0   374.6     .12       0
     431     .06       0  450.32     .12       0
Bank Sta=357.2,374.6
XS Rating Curve= 0 ,0
Exp/Cntr=0.3,0.1

Type RM Length L Ch R = 1 ,21739.9 ,227.5,264.3,293.6
XS GIS Cut Line= 3
     2169811.218      222904.526     2169958.923      222479.666
     2169798.846      222117.882
#Sta/Elev= 30
       0 2304.46    29.3 2283.64      75 2247.92   114.1 2219.12   143.4 2199.73
   153.2 2194.57     163 2191.35     176 2189.71   195.6  2190.9   218.4 2189.74
   231.4  2190.6   466.2 2185.96   485.8 2182.68   502.1 2180.98   508.6 2182.49
   521.7 2196.07   528.3 2198.21   541.4 2197.31     561 2190.85   567.5 2190.64
   619.8 2196.18   636.2 2200.64   655.8 2199.94   737.5  2205.3   744.1 2206.59
   760.4 2213.37   786.6 2216.54   809.4 2217.93   835.6 2216.78   845.4 2218.69
#Mann= 3 ,-1 , 0
       0     .12       0   485.8    .045       0   508.6     .12       0
Bank Sta=485.8,508.6
XS Rating Curve= 0 ,0
Exp/Cntr=0.3,0.1

Type RM Length L Ch R = 1 ,21475.6 ,253,256.5,257.3
XS GIS Cut Line= 2
     2169955.082      222917.393     2170251.014      222195.873
#Sta/Elev= 30
       0 2273.96    81.9 2209.62    91.8 2203.06   114.7 2190.49   134.3 2186.76
     272 2187.26   294.9 2185.86   321.1 2186.58   330.9 2185.25   344.2 2178.88
   350.6 2177.71   363.7 2178.56   383.4 2182.47   399.8 2181.41   416.1 2184.18
   432.5 2184.54   455.5 2189.91   465.3 2191.03   553.8 2192.39   583.2 2194.76
   599.6 2197.74     616 2198.61   625.8 2201.26   642.2 2203.15   668.4 2208.18
   681.6 2211.81   694.7 2217.29   707.8 2217.61   717.6 2222.07   779.8 2237.41
#Mann= 3 ,-1 , 0
       0     .12       0   344.2    .045       0   363.7     .12       0
Bank Sta=344.2,363.7
XS Rating Curve= 0 ,0
Exp/Cntr=0.3,0.1

Type RM Length L Ch R = 1 ,21219.1 ,236.1,232.2,226.8
XS GIS Cut Line= 3
     2170134.841      222975.889     2170324.037       222590.86
     2170543.165      222346.871
#Sta/Elev= 30
       0 2257.26      36 2231.27    55.7 2215.82    75.3  2202.7      95 2191.04
   108.1 2186.71   124.4  2184.8   199.8 2183.42   222.7 2184.19   235.8 2182.79
   284.9 2185.12   320.9 2183.83   353.7 2184.29   360.2 2183.42   383.2 2176.12
     393 2174.86   406.1 2176.44   415.9 2180.97   425.7  2182.6   445.4  2191.5
   458.5  2193.6   494.6 2196.24   540.5 2197.02   553.6 2194.96   566.7 2195.56
   586.4 2193.09   625.8 2196.27   642.2 2200.58     675 2211.51     757 2245.75
#Mann= 3 ,-1 , 0
       0     .12       0   383.2    .045       0   406.1     .12       0
Bank Sta=383.2,406.1
XS Rating Curve= 0 ,0
Exp/Cntr=0.3,0.1

Type RM Length L Ch R = 1 ,20986.9 ,250.6,250,248
XS GIS Cut Line= 3
     2170389.366      223076.593     2170509.372      222732.944
     2170629.377      222389.295
#Sta/Elev= 30
       0 2252.57    26.2 2234.06    65.6 2207.88   101.7 2187.41   121.3 2179.96
   127.9 2179.28     164 2179.22   249.2  2180.5   291.9 2180.15   314.8  2178.2
     341 2178.37   344.3 2177.74   350.9 2174.46   354.2 2172.93     364 2172.57
   371.5 2174.08   393.5  2177.8   406.6  2182.3   432.9 2181.92   449.3 2189.16
   459.1 2191.68   508.3 2194.92   521.4 2196.83   541.1 2196.26   550.9 2198.34
   593.6 2200.93     646 2206.42   655.9 2208.71     669 2213.09     728 2237.16
#Mann= 3 ,-1 , 0
       0     .12       0   350.9    .045       0   371.5     .12       0
Bank Sta=350.9,371.5
XS Rating Curve= 0 ,0
Exp/Cntr=0.3,0.1

Type RM Length L Ch R = 1 ,20736.9 ,258,249.6,242
XS GIS Cut Line= 3
     2170624.426      223178.361     2170750.685      222797.215
     2170852.591      222447.826
#Sta/Elev= 30
       0 2236.13    55.5 2192.96    75.1 2179.43    84.9 2176.16   114.2 2174.72
   130.6 2176.27   176.3 2176.86   205.6 2175.02   270.9 2176.42   336.2 2175.63
   355.8 2173.46   378.7 2172.87   388.5 2171.65   401.5 2169.84   411.4 2171.59
   421.2 2175.95   437.6 2179.43   470.4 2180.95   486.8 2177.29     513 2184.99
   526.1 2182.53   532.7 2182.57   552.3 2188.65     572 2188.42   598.2  2190.9
   627.8 2192.01   650.7 2195.13   696.6 2198.74   719.6 2203.88   765.5  2217.5
#Mann= 3 ,-1 , 0
       0     .12       0   388.5    .045       0   411.4     .12       0
Bank Sta=388.5,411.4
XS Rating Curve= 0 ,0
Exp/Cntr=0.3,0.1