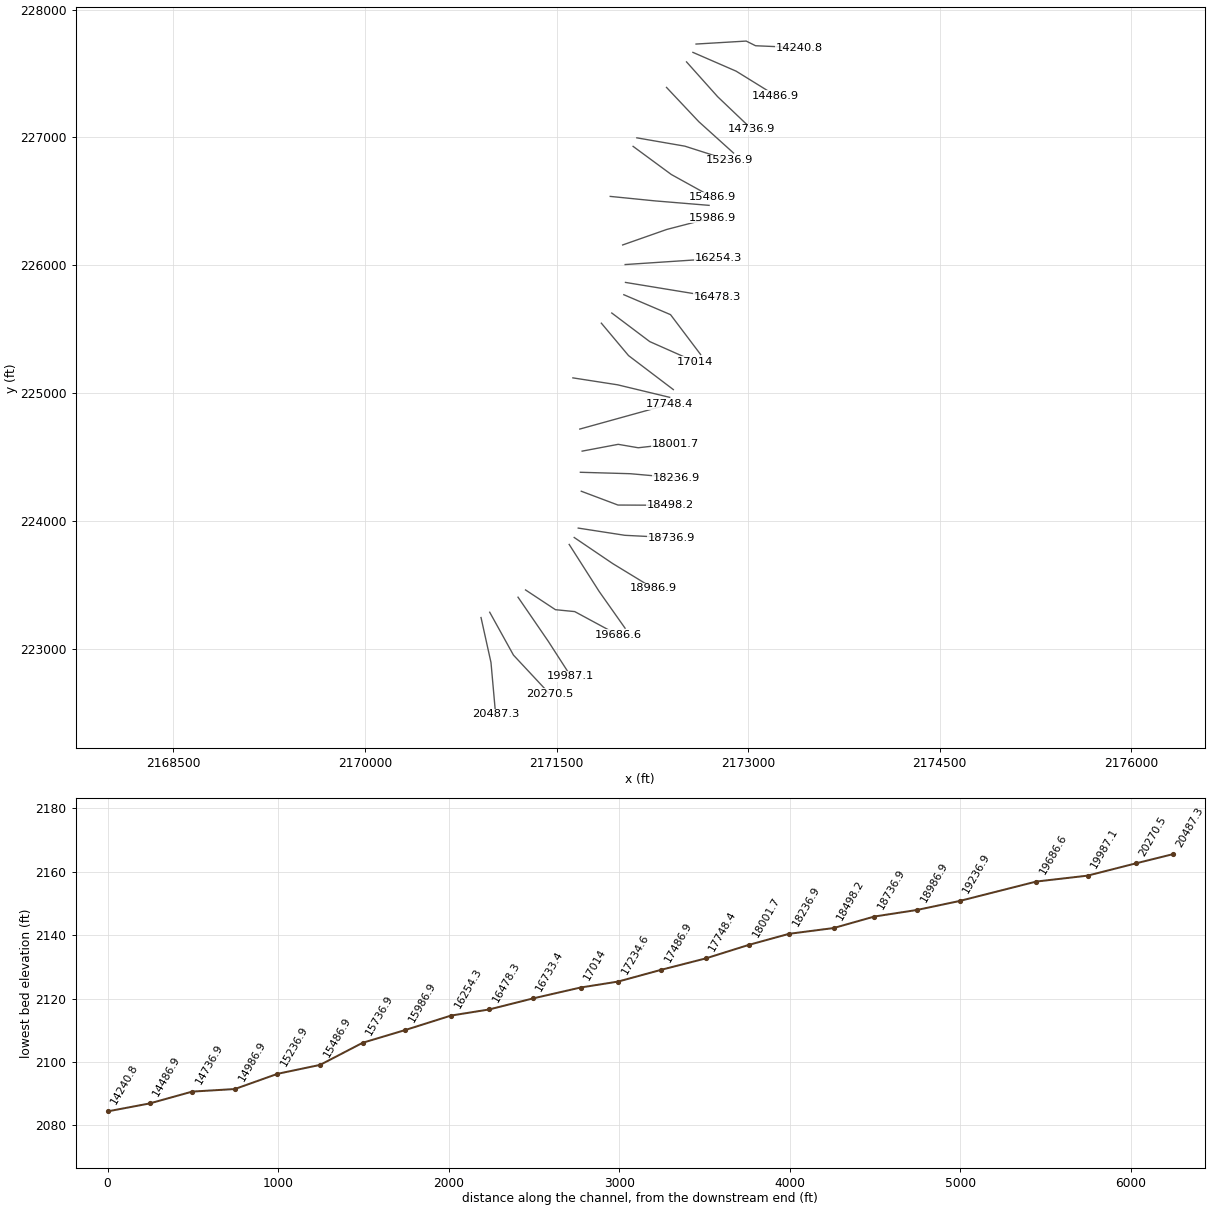
HEC-RAS study BACKCK2.prj: BACKCK2

--- BACKCK2.g01 (geometry) --- (continued)

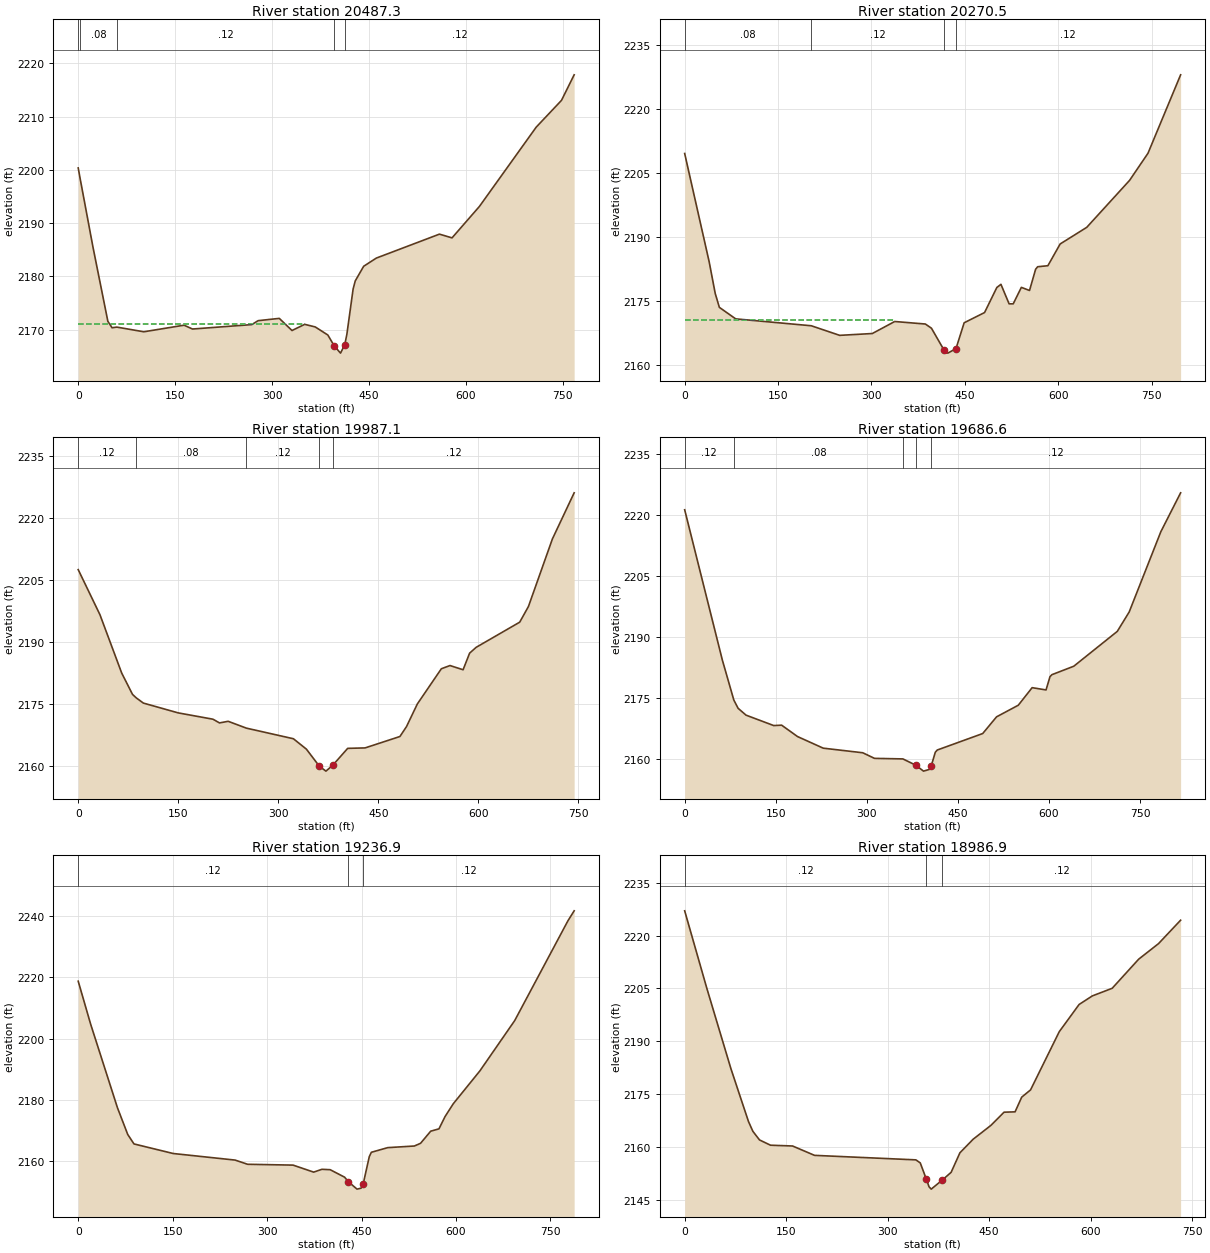
Type RM Length L Ch R = 1 ,20487.3 ,191.6,216.8,241.5
XS GIS Cut Line= 3
     2170908.219      223246.405      2170986.22      222894.568
     2171022.472      222489.016
#Sta/Elev= 30
       0 2200.37    3.052198.327    22.9 2185.46    45.9 2171.55    52.4 2170.34
    59.8 2170.46   101.6 2169.58   163.8 2170.82   176.9  2170.1   268.6 2170.93
   278.5 2171.67   311.2  2172.1   330.9 2169.82   350.6 2170.98   366.9 2170.49
   386.4 2168.97   396.2 2166.94     406 2165.57   412.5 2167.13   415.8 2169.09
   425.5 2177.62   428.8 2179.14   441.8 2181.89   461.4 2183.43   559.1 2187.93
   578.6 2187.23     621 2193.14   708.9 2208.04     748 2213.07   767.6 2217.87
#Mann= 5 ,-1 , 0
       0     .12       0    3.05     .08       0    59.8     .12       0
   396.2    .045       0   412.5     .12       0
#XS Ineff= 2 , 0
          351.18 2171.02
Permanent Ineff=
       F       F
Bank Sta=396.2,412.5
XS Rating Curve= 0 ,0
Exp/Cntr=0.3,0.1

Type RM Length L Ch R = 1 ,20270.5 ,289,283.4,277.7
XS GIS Cut Line= 3
     2170976.263      223287.895     2171162.139      222952.654
     2171444.272      222650.606
#Sta/Elev= 30
       0 2209.52    39.3 2184.14    49.1 2176.66    55.7 2173.42    81.9 2170.72
  203.322169.102     249 2166.85   301.4 2167.28   337.4  2170.1   386.6 2169.51
   396.4 2168.52   416.1 2163.52   422.7 2162.68   435.8 2163.74   448.9  2169.8
   481.7  2172.2   501.4 2178.08     508 2178.82   521.1 2174.25   527.7 2174.24
   540.8 2178.11   553.9 2177.38   563.7 2182.36     567 2182.95   583.4 2183.19
   603.1 2188.29   645.8 2192.19   714.6 2203.21   744.2 2209.58   796.6 2227.98
#Mann= 4 ,-1 , 0
       0     .08       0  203.32     .12       0   416.1    .045       0
   435.8     .12       0
#XS Ineff= 2 , 0
          335.94 2170.36
Permanent Ineff=
       F       F
Bank Sta=416.1,435.8
XS Rating Curve= 0 ,0
Exp/Cntr=0.3,0.1

Type RM Length L Ch R = 1 ,19987.1 ,266.7,300.5,333.4
XS GIS Cut Line= 3
     2171197.844      223405.522     2171433.955      223061.772
     2171611.038      222787.466
#Sta/Elev= 30
       0 2207.58    32.6 2196.66    65.2 2182.54    81.4 2177.38    86.72176.574
    97.7 2175.27   149.9  2172.9     202 2171.37   211.8 2170.47   224.8 2170.86
  252.112169.208   322.6 2166.64   342.1 2164.12   361.6 2159.97   371.4  2158.8
   381.6 2160.22     404 2164.31   430.1 2164.42   482.3 2167.18   492.1 2169.56
   508.4 2175.05   544.4 2183.58   557.4 2184.36     577 2183.34   586.8 2187.36
   596.6 2188.77   661.9 2194.86     675 2198.66   710.9 2215.01   743.5 2226.17
#Mann= 5 ,-1 , 0
       0     .12       0    86.7     .08       0  252.11     .12       0
   361.6    .045       0   381.6     .12       0
Bank Sta=361.6,381.6
XS Rating Curve= 0 ,0
Exp/Cntr=0.3,0.1

Type RM Length L Ch R = 1 ,19686.6 ,482.7,449.7,394.7
XS GIS Cut Line= 4
     2171256.736      223462.154     2171490.741       223307.81
     2171641.765      223292.874     2171980.325      223110.317
#Sta/Elev= 30
       0 2221.26    61.9 2184.35   80.942174.431      88  2172.4     101 2170.72
   146.7 2168.15   159.7 2168.25   185.8 2165.45   228.2 2162.59   293.2 2161.46
   312.6 2160.08  359.372159.946   380.4 2158.41   393.3 2156.94     403 2157.36
   406.2 2158.31   412.7 2161.58   415.9 2162.13   490.8 2166.19   513.6  2170.3
   549.4 2173.16   572.2 2177.48   595.1 2176.92   601.6 2180.19   604.8 2180.68
   640.7 2182.75   712.4 2191.33     732  2196.1   784.1 2215.85   816.7 2225.43
#Mann= 5 ,-1 , 0
       0     .12       0   80.94     .08       0  359.37     .12       0
   380.4    .045       0   406.2     .12       0
Bank Sta=380.4,406.2
XS Rating Curve= 0 ,0
Exp/Cntr=0.3,0.1

Type RM Length L Ch R = 1 ,19236.9 ,234,250,265.3
XS GIS Cut Line= 3
     2171598.476      223817.943     2171833.178      223450.147
     2172035.874      223163.106
#Sta/Elev= 30
       0 2218.77    19.7 2204.76    62.3 2177.43    78.7 2168.66    88.6 2165.58
   150.9 2162.45   249.3  2160.3     269 2158.93   341.2 2158.66     374 2156.37
   387.1 2157.29   400.2 2157.16   423.2  2154.7   428.8 2153.29   442.8 2150.81
   449.3 2151.12   452.6 2152.47   462.3 2161.42   465.6 2162.85   491.6 2164.37
   533.9  2164.9   543.7 2165.78   559.9 2169.75     573 2170.51   582.7 2174.54
   595.7 2178.71     638 2189.46   693.3  2205.9   777.9 2238.54   787.7 2241.77
#Mann= 3 ,-1 , 0
       0     .12       0   428.8    .045       0   452.6     .12       0
Bank Sta=428.8,452.6
XS Rating Curve= 0 ,0
Exp/Cntr=0.3,0.1

Type RM Length L Ch R = 1 ,18986.9 ,233.1,250,268.4
XS GIS Cut Line= 3
     2171637.745      223872.249     2171939.523      223668.114
     2172254.222      223476.448
#Sta/Elev= 30
       0 2227.01    32.5 2205.16    68.3 2182.19    94.3 2167.16   100.8 2164.38
   110.6 2161.94   126.9 2160.44   159.4 2160.22   191.9 2157.56   341.6 2156.28
   348.1 2155.42   356.8 2150.94   361.1 2148.63   364.3 2147.97   380.6 2150.54
   393.7 2152.74   406.7 2158.29   426.3 2162.15   452.4 2166.06   471.9 2169.82
   488.2 2169.92     498 2174.09   511.1 2176.16   553.5 2192.69   582.8 2200.41
   602.4 2202.85   631.7 2205.01   670.8 2213.27   700.2  2217.7   732.8 2224.35
#Mann= 3 ,-1 , 0
       0     .12       0   356.8    .045       0   380.6     .12       0
Bank Sta=356.8,380.6
XS Rating Curve= 0 ,0
Exp/Cntr=0.3,0.1

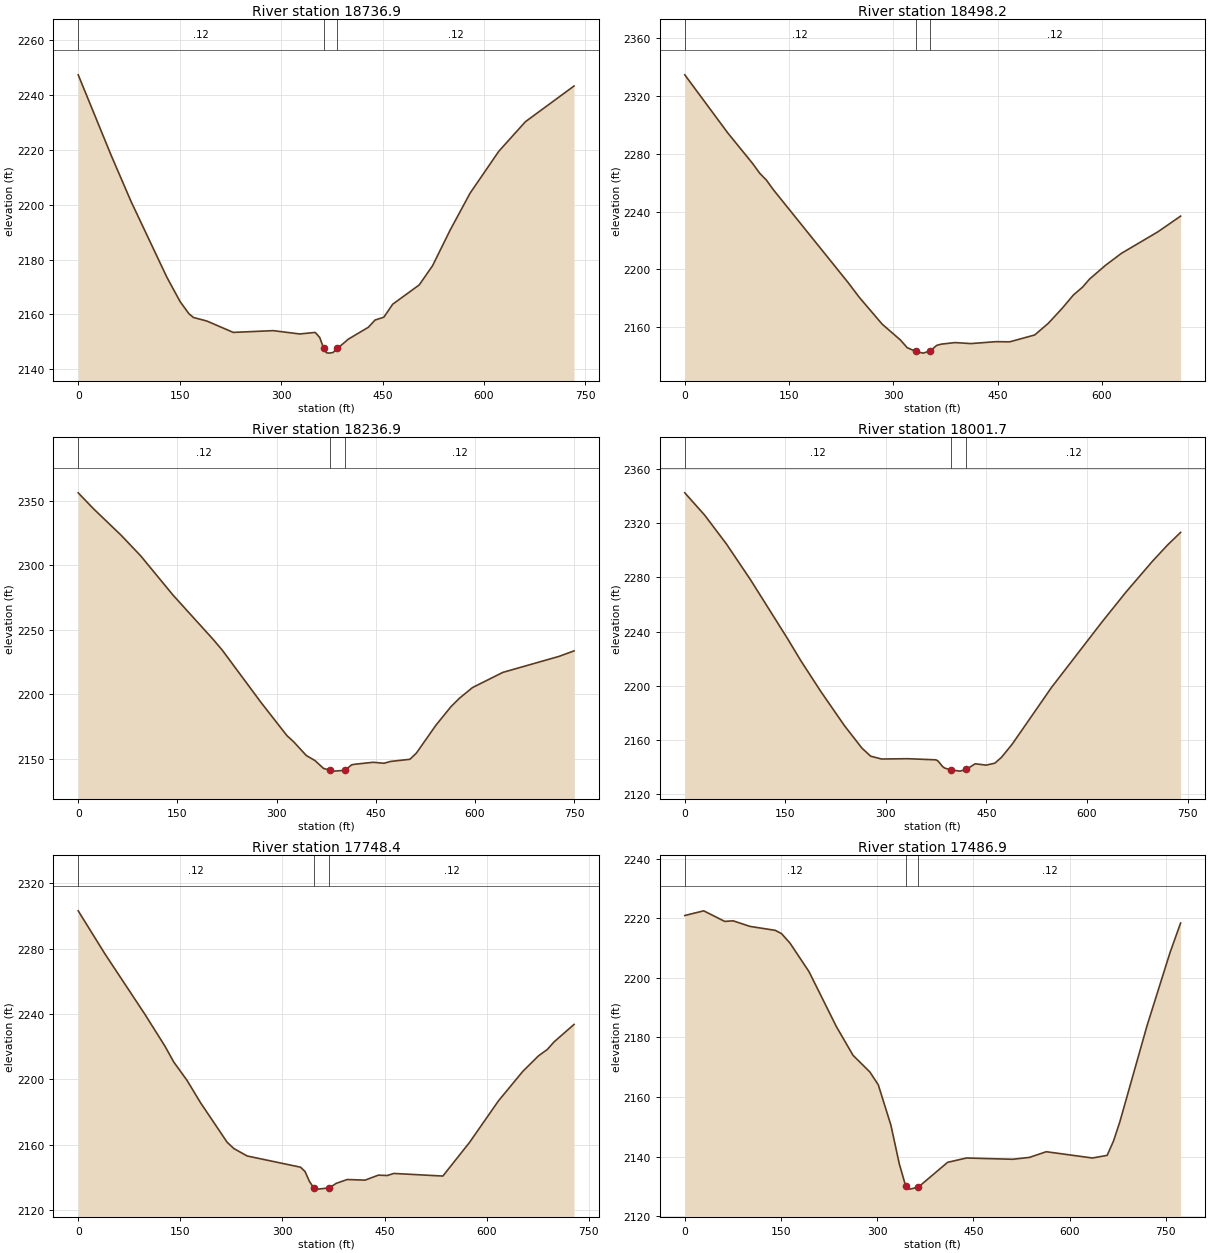
Type RM Length L Ch R = 1 ,18736.9 ,236,238.7,240.5
XS GIS Cut Line= 3
     2171669.255      223945.801     2172035.114      223889.291
     2172397.549        223870.8
#Sta/Elev= 30
       0 2247.39    49.1 2217.81    78.6 2200.96     131 2173.63   150.7 2164.67
   163.8 2160.25   170.4  2158.9     190 2157.62   229.3 2153.46   288.3  2154.1
   327.6 2152.89   350.5 2153.45   357.1  2151.6   362.7 2147.83   366.9 2146.07
   370.2  2145.9   376.7 2146.11   383.3  2147.6   399.6 2151.03     429 2155.33
   438.9 2157.97   451.9 2159.01     465 2163.74   504.2 2170.77   523.9 2177.77
     550  2190.8   579.4 2204.23   621.9 2219.52   661.2 2230.29   733.1 2243.32
#Mann= 3 ,-1 , 0
       0     .12       0   362.7    .045       0   383.3     .12       0
Bank Sta=362.7,383.3
XS Rating Curve= 0 ,0
Exp/Cntr=0.3,0.1

Type RM Length L Ch R = 1 ,18498.2 ,259.3,261.3,257.1
XS GIS Cut Line= 3
     2171693.213      224233.871     2171980.325      224125.997
     2172386.684      224124.302
#Sta/Elev= 30
       0 2334.38      62 2294.16    97.9 2272.97   107.7 2266.46   117.5 2261.64
   127.2 2255.18   234.9 2190.96   251.2 2180.66   283.9 2162.25     310  2151.4
   319.8 2146.06   332.1 2143.43   342.8 2142.27   352.6 2143.73   362.4 2147.64
     369 2148.48   388.6 2149.55   411.6 2148.86   447.6 2150.18   467.3 2150.07
   503.3 2154.81     523 2162.95   542.7 2173.18     559 2182.44   572.2 2187.88
     582 2193.33   604.9 2202.83   627.9 2211.13   680.3 2225.98   713.1 2236.85
#Mann= 3 ,-1 , 0
       0     .12       0   332.1    .045       0   352.6     .12       0
Bank Sta=332.1,352.6
XS Rating Curve= 0 ,0
Exp/Cntr=0.3,0.1

Type RM Length L Ch R = 1 ,18236.9 ,240.2,235.2,231.8
XS GIS Cut Line= 3
     2171686.037      224382.197     2172076.316      224371.025
       2172434.2      224339.433
#Sta/Elev= 30
       0 2356.34    22.8 2344.15    65.1 2323.33    94.4  2307.5   143.2 2277.11
     205 2242.09     218 2234.19   276.6  2193.6   315.6    2168   325.4 2163.43
   344.9 2152.55   357.9  2148.7   370.9 2142.57   380.7  2141.1   387.2 2140.45
   403.5 2141.12   413.3 2145.28   416.6 2145.69     446 2147.31   462.3 2146.54
   472.1 2147.95   501.5 2149.64   511.3 2154.42   540.7 2175.95   563.5 2190.38
   576.6 2197.08   596.2 2205.27   641.9 2217.02   726.8 2229.43   749.7 2233.74
#Mann= 3 ,-1 , 0
       0     .12       0   380.7    .045       0   403.5     .12       0
Bank Sta=380.7,403.5
XS Rating Curve= 0 ,0
Exp/Cntr=0.3,0.1

Type RM Length L Ch R = 1 ,18001.7 ,236.7,253.3,269.8
XS GIS Cut Line= 4
     2171699.851      224547.537     2171981.992      224600.752
     2172138.816      224573.924     2172430.483      224606.911
#Sta/Elev= 30
       0 2342.39    29.4 2326.07      62 2304.73    97.9 2278.34   153.4 2234.68
   172.9 2218.65   202.3 2196.22   238.2 2170.52   264.3 2153.93   277.3 2147.99
   293.6 2145.91   332.6 2146.14   374.8  2145.3     378 2144.35   384.5 2140.39
   387.8 2139.19   397.5 2137.84   410.5 2136.97   420.2 2138.29   433.2  2142.4
   449.5  2141.4   462.5 2142.83   472.3 2147.06   488.6 2156.99   547.3 2198.89
   622.3    2247   658.2 2269.14   697.3 2291.68   720.2 2303.88   739.7  2313.2
#Mann= 3 ,-1 , 0
       0     .12       0   397.5    .045       0   420.2     .12       0
Bank Sta=397.5,420.2
XS Rating Curve= 0 ,0
Exp/Cntr=0.3,0.1

Type RM Length L Ch R = 1 ,17748.4 ,277.2,261.5,242.1
XS GIS Cut Line= 2
     2171681.596      224720.136      2172383.61       224914.31
#Sta/Elev= 30
       0 2303.14    39.2 2276.82      98 2239.76   127.4 2220.29   140.4 2210.53
     160 2199.22   179.6 2185.68   218.8  2161.4   228.6 2157.57   248.2 2152.99
   326.6 2146.13   333.2  2143.5   339.7 2137.41   346.2 2133.35   352.8 2132.69
   369.1  2133.5   378.9  2136.2   395.2 2138.58   421.4  2138.2   440.9 2141.25
     454 2141.04   463.8 2142.29   535.7  2140.7   574.9 2161.31   617.3 2186.71
   653.2 2204.84   676.1 2214.29   689.2 2218.24     699 2222.84   728.4 2233.57
#Mann= 3 ,-1 , 0
       0     .12       0   346.2    .045       0   369.1     .12       0
Bank Sta=346.2,369.1
XS Rating Curve= 0 ,0
Exp/Cntr=0.3,0.1

Type RM Length L Ch R = 1 ,17486.9 ,273.9,252.3,236.8
XS GIS Cut Line= 3
     2171627.373      225120.367     2171977.487      225066.124
     2172384.923      224968.299
#Sta/Elev= 30
       0 2220.96    29.5 2222.53    62.3 2218.98    75.4 2219.17   101.7  2217.3
   141.1 2215.98   150.9 2214.87     164 2211.71   193.6 2202.16   236.2 2183.75
   262.4 2174.02   288.7 2168.41   301.8  2164.1   321.5 2150.53   334.6 2137.53
   344.4  2130.2     351 2129.09   364.1 2129.74   409.9 2138.09   439.4 2139.54
   511.4 2139.11   537.6 2139.75   563.8 2141.65   635.8 2139.54   658.7 2140.43
   668.6 2145.23   678.4 2151.61   720.9 2183.95   756.9  2208.6   773.3 2218.44
#Mann= 3 ,-1 , 0
       0     .12       0   344.4    .045       0   364.1     .12       0
Bank Sta=344.4,364.1
XS Rating Curve= 0 ,0
Exp/Cntr=0.3,0.1

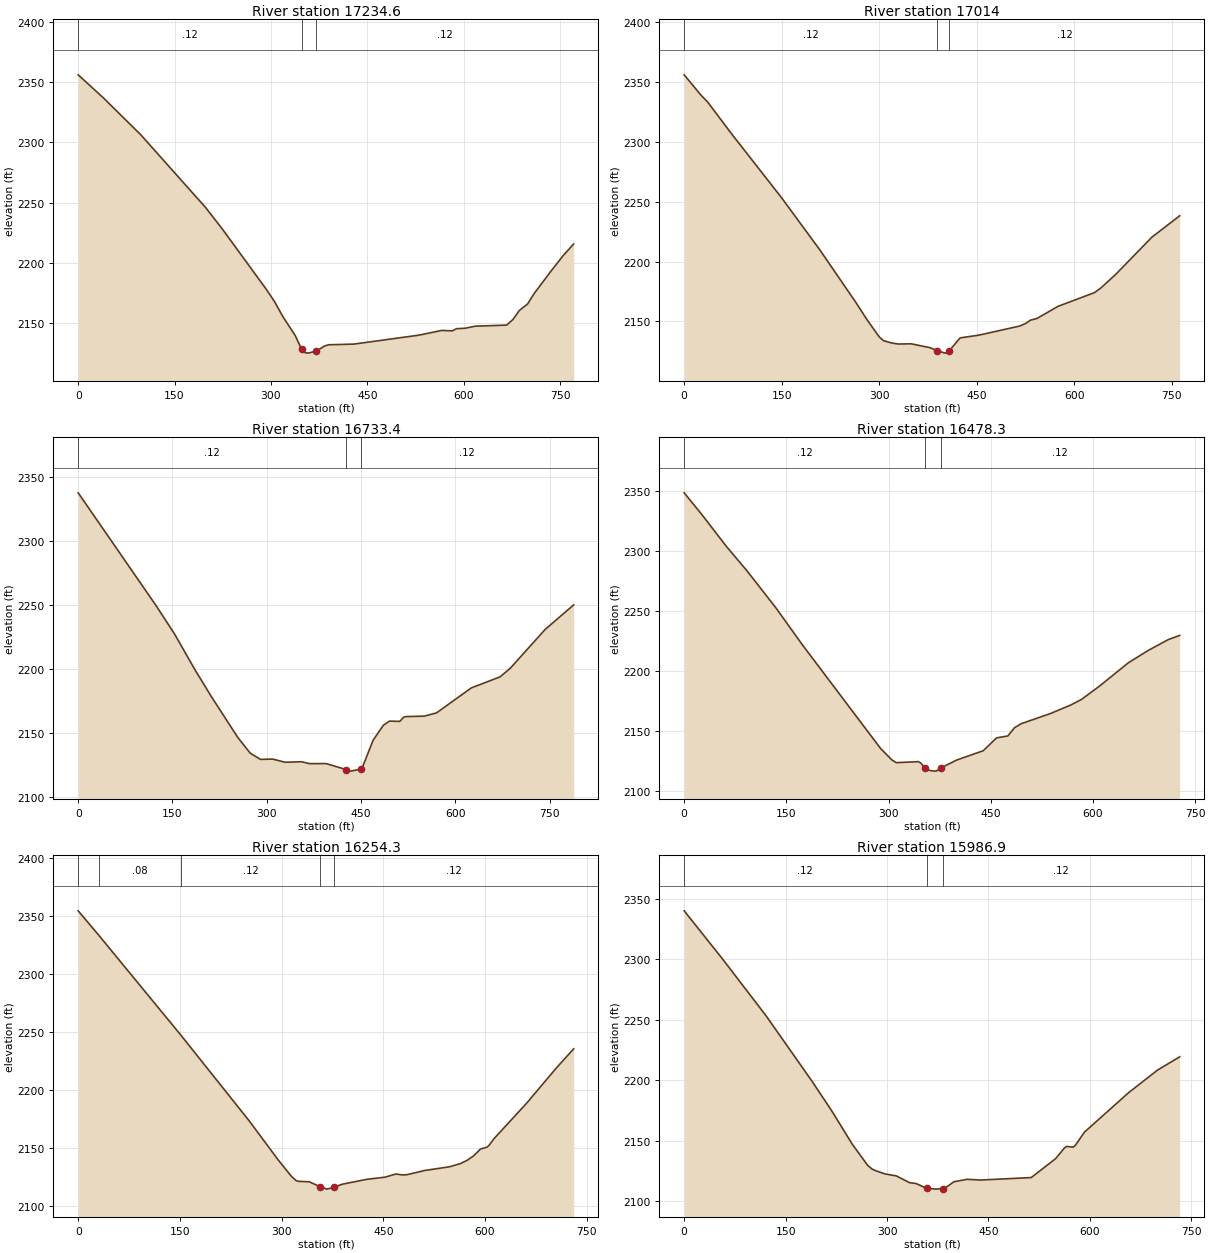
Type RM Length L Ch R = 1 ,17234.6 ,211.6,220.6,228.7
XS GIS Cut Line= 3
     2171850.137      225548.076     2172063.306      225294.361
      2172413.83      225028.715
#Sta/Elev= 30
       0 2356.02      39 2337.04    97.5 2306.29   198.2 2246.13   224.2 2228.34
   292.4 2178.55   305.4 2168.26   318.4 2155.78   337.9 2139.87   347.8 2128.45
   350.9 2126.17   357.4 2125.38   370.5 2126.98   383.5 2131.29     390 2132.31
   429.1 2132.86   530.1 2140.26     566 2144.21   582.2 2143.82   588.8 2145.62
   601.8 2145.96   618.1 2147.72   666.9  2148.6   676.7 2153.28   686.5 2160.66
   699.5 2166.19   709.3 2174.47   735.4 2193.04   754.9 2206.24   771.2 2215.87
#Mann= 3 ,-1 , 0
       0     .12       0   347.8    .045       0   370.5     .12       0
Bank Sta=347.8,370.5
XS Rating Curve= 0 ,0
Exp/Cntr=0.3,0.1

Type RM Length L Ch R = 1 ,17014   ,295,280.6,261.4
XS GIS Cut Line= 3
     2171931.881      225627.469     2172229.266      225403.895
     2172586.169      225245.874
#Sta/Elev= 30
       0 2356.04    26.1 2338.92    35.9 2333.49    71.8 2307.54   150.1 2253.17
   208.9 2209.65   264.4 2165.69   280.7 2151.95   300.2 2136.98   306.8  2133.9
   319.8  2131.9   329.6  2131.1   349.2  2131.3   378.6 2128.02   388.4 2125.66
   401.6  2123.5   404.8 2123.94   408.1 2125.55   424.5 2136.22     454 2138.57
   516.4 2146.16   526.2 2148.53   532.8 2151.06   542.6  2152.4   575.4 2162.64
   631.2 2174.02     641 2177.88     664  2189.3   719.7 2220.43   762.4 2238.27
#Mann= 3 ,-1 , 0
       0     .12       0   388.4    .045       0   408.1     .12       0
Bank Sta=388.4,408.1
XS Rating Curve= 0 ,0
Exp/Cntr=0.3,0.1

Type RM Length L Ch R = 1 ,16733.4 ,226.1,255.1,284.1
XS GIS Cut Line= 3
     2172026.107      225770.636     2172391.908      225614.665
     2172627.488      225302.895
#Sta/Elev= 30
       0 2337.93   123.9 2249.65   153.2 2227.53   185.8  2199.4   211.9  2178.4
   254.2 2146.23   273.8 2134.08   290.1 2129.23   309.7 2129.47   329.2 2126.97
   355.3 2127.38   368.3  2125.9   394.4 2125.94   426.6 2121.23   433.5 2120.04
   449.8 2121.59     453    2124   469.3 2144.26   485.6 2155.98   495.4 2159.22
   511.6 2158.97   518.2 2162.36   521.4 2162.73   550.7  2163.1   570.2 2165.65
   625.6 2185.22   671.2 2193.83   687.5 2200.58   742.8 2230.88   788.4 2250.22
#Mann= 3 ,-1 , 0
       0     .12       0   426.6    .045       0   449.8     .12       0
Bank Sta=426.6,449.8
XS Rating Curve= 0 ,0
Exp/Cntr=0.3,0.1

Type RM Length L Ch R = 1 ,16478.3 ,214.9,224,232
XS GIS Cut Line= 2
     2172039.221      225866.748     2172757.022      225749.093
#Sta/Elev= 30
       0 2348.76    26.2 2330.44    62.2 2303.89    91.7 2284.05   134.3 2253.08
   173.6  2221.9   288.3  2135.5   304.7 2126.03   311.3 2123.64     344 2124.49
   347.3 2123.33   353.9 2119.03   357.1 2117.47     367 2116.58   370.2 2116.65
   376.8  2119.2   399.7 2125.75     439  2133.6   458.7 2144.37   475.1  2145.9
   484.9 2152.75   494.8 2156.16   537.3 2164.54   566.8 2171.54   583.2 2176.38
   609.4 2187.37     652 2206.95   681.5 2217.36     711 2226.41   727.4 2229.78
#Mann= 3 ,-1 , 0
       0     .12       0   353.9    .045       0   376.8     .12       0
Bank Sta=353.9,376.8
XS Rating Curve= 0 ,0
Exp/Cntr=0.3,0.1

Type RM Length L Ch R = 1 ,16254.3 ,256.2,267.4,275
XS GIS Cut Line= 2
     2172036.523      226006.443     2172765.693      226054.805
#Sta/Elev= 30
       0 2354.64   30.192333.719  151.052247.728   252.3 2173.46   294.9 2139.93
   314.6 2125.61   321.2  2122.1   324.4 2121.38   340.8 2120.99   357.2  2116.6
     367 2114.65   376.9 2116.27     390 2118.95     426 2123.13   452.2 2124.92
   468.6 2127.69   478.4 2126.88     485  2127.1   511.2 2130.75   547.3 2133.87
   563.6 2136.65   573.5 2139.45   583.3  2143.4   593.1 2149.11     603 2150.82
   606.2 2152.56   612.8 2157.84     662 2189.15   704.6  2218.7   730.8 2235.67
#Mann= 5 ,-1 , 0
       0     .12       0   30.19     .08       0  151.05     .12       0
   357.2    .045       0   376.9     .12       0
Bank Sta=357.2,376.9
XS Rating Curve= 0 ,0
Exp/Cntr=0.3,0.1

Type RM Length L Ch R = 1 ,15986.9 ,266.4,250,236.9
XS GIS Cut Line= 3
     2172017.083      226159.687     2172362.425      226280.929
     2172717.574      226372.932
#Sta/Elev= 30
       0 2340.24    55.6 2301.25   120.9 2253.61   189.5 2199.01     219 2174.18
   248.4 2147.44   271.2 2129.92   277.8 2126.72   284.3 2125.11   297.4 2122.64
   313.7 2121.05   333.3 2115.45   343.1 2114.71   358.5 2110.81   372.6  2110.1
   382.4 2110.56   385.7 2110.87   398.8 2116.15   418.4 2118.23   438.1 2117.61
   513.4 2119.67   549.4 2135.31   562.5 2144.17   565.8 2145.42   575.6 2144.81
   578.9 2146.54     592 2157.22   657.5 2189.93   700.1 2208.51   732.9 2219.51
#Mann= 3 ,-1 , 0
       0     .12       0   358.5    .045       0   382.4     .12       0
Bank Sta=358.5,382.4
XS Rating Curve= 0 ,0
Exp/Cntr=0.3,0.1

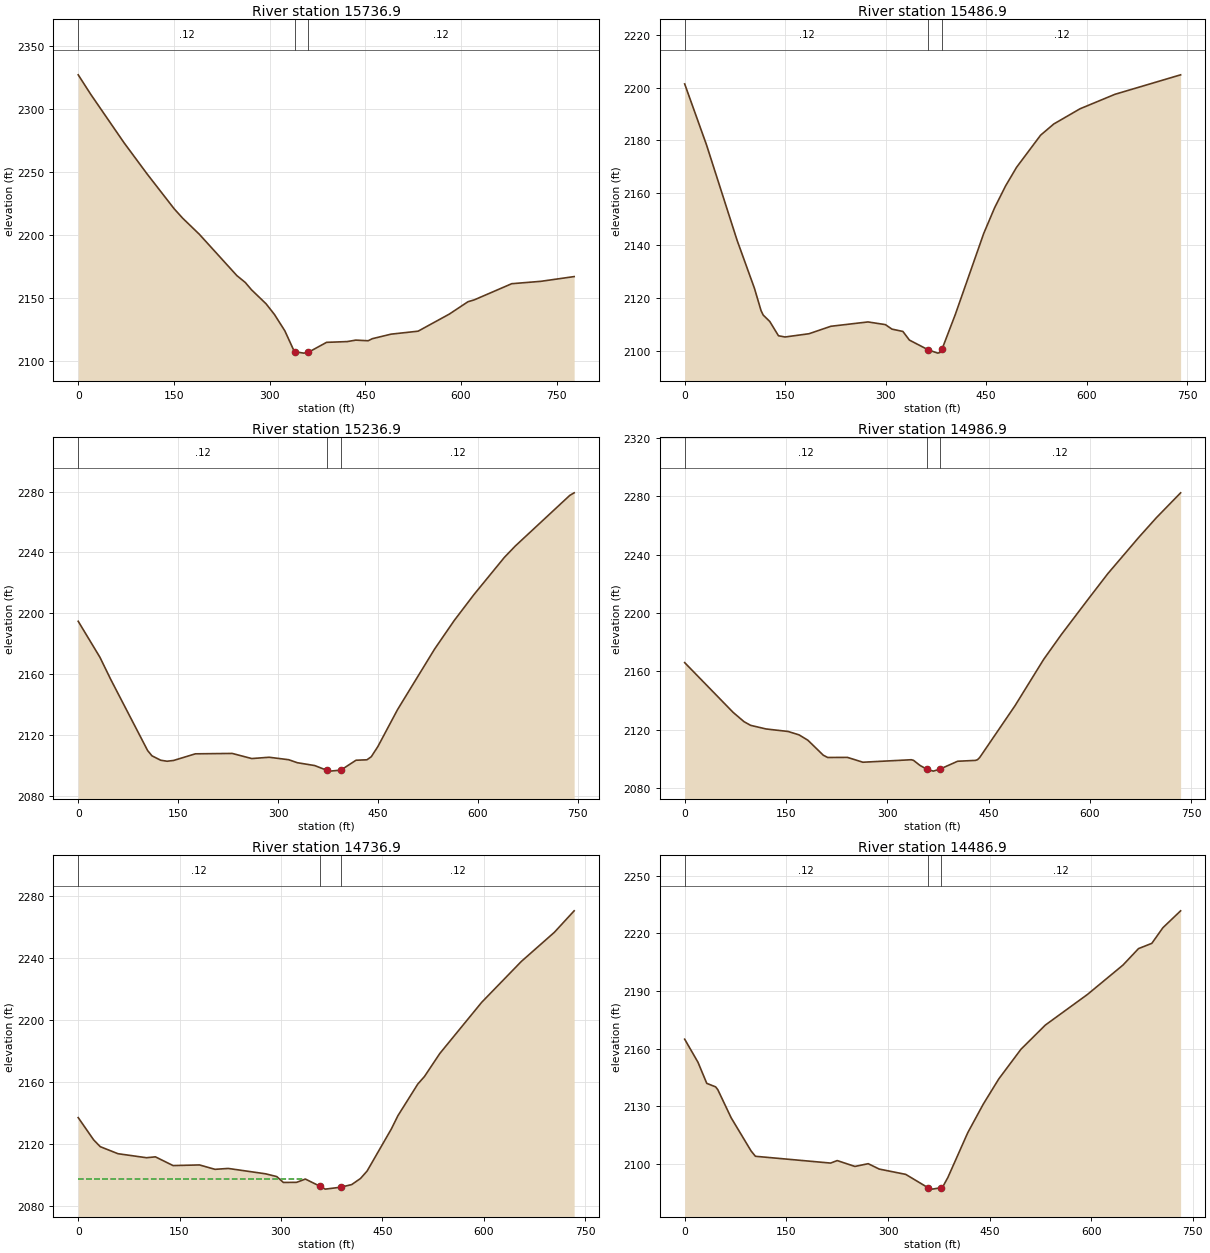
Type RM Length L Ch R = 1 ,15736.9 ,269.5,250,234.6
XS GIS Cut Line= 3
     2171919.685      226539.325     2172271.355      226504.158
     2172693.847      226469.282
#Sta/Elev= 30
       0 2326.86    19.6 2311.43      72 2272.86     108 2248.23   150.5 2220.54
   163.6  2213.2   189.8 2200.41   248.7 2167.58   261.8 2162.18   271.6 2156.35
   294.5  2145.2   307.6 2136.76     324 2123.69   337.1 2109.16   340.3 2107.16
   353.4 2106.08   360.9 2106.78   389.3 2114.63   421.9 2115.24     435  2116.4
   454.5  2115.9     461 2117.53   490.4 2121.13   532.8 2123.49   581.7 2137.04
     611 2146.86   620.8 2148.32   679.5 2161.15   725.2 2163.04   777.4  2166.8
#Mann= 3 ,-1 , 0
       0     .12       0   340.3    .045       0   360.9     .12       0
Bank Sta=340.3,360.9
XS Rating Curve= 0 ,0
Exp/Cntr=0.3,0.1

Type RM Length L Ch R = 1 ,15486.9 ,232.6,250,256.2
XS GIS Cut Line= 3
     2172098.799      226930.487     2172397.968      226710.576
     2172720.986      226532.246
#Sta/Elev= 30
       0 2201.37    32.6 2178.21    78.2 2141.99   104.2 2123.68     114 2115.24
   117.2 2113.56     127 2111.12     140 2105.69   149.8 2105.22   185.6 2106.46
   218.2 2109.29   273.6 2110.94   299.6 2109.92   309.4 2108.21   325.7 2107.33
   335.5 2104.04   363.8 2100.31   377.8 2099.09   381.1 2099.32   384.4 2100.76
     404 2113.79   446.4 2144.57   462.7 2154.35     479 2162.61   495.4 2169.69
   531.3  2181.9   550.9 2186.14   590.1 2191.92   642.3 2197.43   740.3 2204.83
#Mann= 3 ,-1 , 0
       0     .12       0   363.8    .045       0   384.4     .12       0
Bank Sta=363.8,384.4
XS Rating Curve= 0 ,0
Exp/Cntr=0.3,0.1

Type RM Length L Ch R = 1 ,15236.9 ,274.2,250,233.6
XS GIS Cut Line= 3
     2172128.161       226997.24     2172503.593      226932.273
     2172849.765      226821.789
#Sta/Elev= 30
       0 2194.77    32.6 2171.12    48.8 2156.56   104.2 2109.79   110.7 2106.33
   123.8 2103.43   133.5 2102.77   143.3  2103.3   175.8 2107.64   231.2  2107.9
   260.5 2104.53   286.6 2105.39   315.9 2103.77   328.9  2101.8     355 2099.93
   373.5 2096.76   377.8 2096.27   394.1 2096.92     417 2103.43   433.4 2103.72
   439.9 2105.74   449.8 2112.43   479.2 2136.62   534.9 2176.49   564.3 2195.22
   593.8 2212.21   639.6 2236.74     656 2244.22   737.8 2277.51   744.4 2279.21
#Mann= 3 ,-1 , 0
       0     .12       0   373.5    .045       0   394.1     .12       0
Bank Sta=373.5,394.1
XS Rating Curve= 0 ,0
Exp/Cntr=0.3,0.1

Type RM Length L Ch R = 1 ,14986.9 ,250.5,250,248.8
XS GIS Cut Line= 3
     2172360.459      227391.499     2172612.917      227123.763
     2172884.876      226878.618
#Sta/Elev= 30
       0 2165.87    71.6 2131.81    87.9 2125.36    97.7 2122.85   120.5 2120.38
   153.1 2118.66   169.3 2116.33   182.4 2112.65   205.2 2102.38   211.7 2100.83
     241 2100.89   263.8 2097.57   335.4 2099.28   338.7 2098.87   348.4 2095.36
   358.2 2092.86     368 2091.47   377.8 2092.84     404 2098.24   430.1 2098.82
   433.4 2099.28   436.6 2100.74     489 2136.35   531.4  2168.1   557.6 2185.14
   596.8 2209.09   626.2  2226.8     672 2251.68   698.2 2265.23   734.1  2282.3
#Mann= 3 ,-1 , 0
       0     .12       0   358.2    .045       0   377.8     .12       0
Bank Sta=358.2,377.8
XS Rating Curve= 0 ,0
Exp/Cntr=0.3,0.1

Type RM Length L Ch R = 1 ,14736.9 ,233.7,250,257.4
XS GIS Cut Line= 3
     2172517.129      227590.997     2172760.935      227318.609
     2173027.829      227064.711
#Sta/Elev= 30
       0 2136.91    22.8 2122.54    32.6 2118.12    58.8 2113.57   101.2 2110.96
   114.2 2111.54   140.4 2105.89   179.5  2106.3   202.4 2103.46     222 2104.04
   277.4 2100.55   293.8 2098.78   303.6 2094.98   323.1 2095.05   336.2 2097.16
   358.1 2092.45   365.6 2090.66   388.4  2091.9   404.7  2093.6   417.7 2097.53
   427.5 2102.35   463.4 2129.58   473.1 2138.14   502.5  2158.6   512.3 2163.44
   535.1 2178.37     597 2211.43   655.7 2237.88   704.6 2256.73   733.9 2270.63
#Mann= 3 ,-1 , 0
       0     .12       0   358.1    .045       0   388.4     .12       0
#XS Ineff= 2 , 0
          335.16 2097.18
Permanent Ineff=
       F       F
Bank Sta=358.1,388.4
XS Rating Curve= 0 ,0
Exp/Cntr=0.3,0.1

Type RM Length L Ch R = 1 ,14486.9 ,248.1,246.1,249.7
XS GIS Cut Line= 3
     2172567.024      227665.514     2172905.174      227518.688
     2173214.167       227327.84
#Sta/Elev= 30
       0 2164.91    19.6 2152.93    32.6 2141.94    45.7 2140.11    48.9 2138.64
    68.5 2124.08    97.9 2106.83   104.4    2104   215.3 2100.47   225.1 2101.77
   251.2 2098.72   270.8 2100.15   287.1 2097.35   326.2 2094.59   358.9 2087.69
   365.4 2086.92   378.5 2087.67   381.7  2088.7   388.3 2092.93   417.7 2116.26
   440.6 2131.13   463.5 2144.25   496.2 2159.67   532.2 2172.26   594.4  2188.2
   646.8 2203.48   669.7 2212.04   689.3 2214.76   705.6 2222.87   731.8 2231.68
#Mann= 3 ,-1 , 0
       0     .12       0   358.9    .045       0   378.5     .12       0
Bank Sta=358.9,378.5
XS Rating Curve= 0 ,0
Exp/Cntr=0.3,0.1

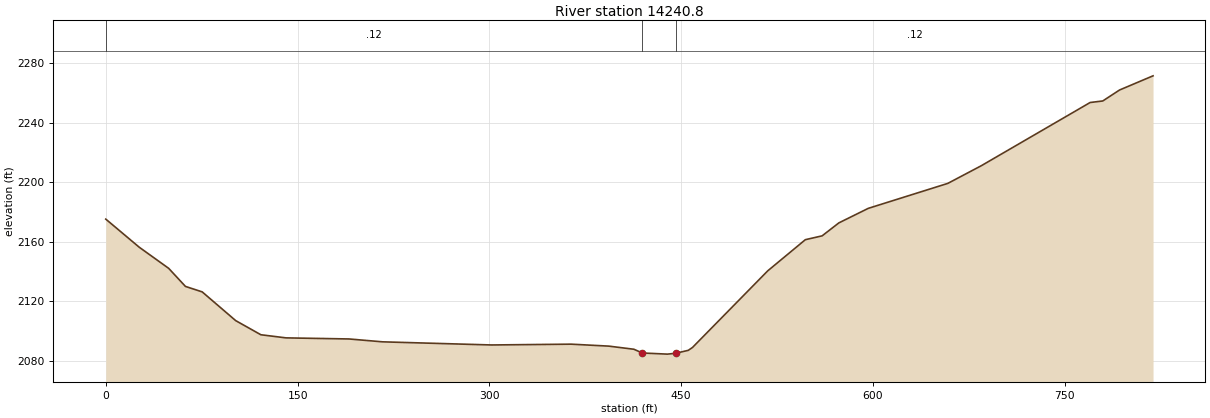
Type RM Length L Ch R = 1 ,14240.8 ,208.4,256.3,305.6
XS GIS Cut Line= 4
     2172591.626      227730.587     2172984.388      227753.899
     2173057.411      227717.388     2173400.949      227702.451
#Sta/Elev= 30
       0 2175.24    26.2 2156.31    49.2 2142.12    62.3 2129.97    75.4 2126.29
   101.6 2106.96   121.3 2097.45     141 2095.35   190.2 2094.62   216.4 2092.69
   301.6 2090.58   363.9 2091.12   393.4  2089.8     413  2087.7   419.6 2085.18
   439.2 2084.42   445.7    2085   455.5 2086.96   458.8 2088.87   517.7 2140.46
   547.1 2161.41   560.2 2163.98   573.3  2172.7   596.3 2182.48   658.5 2199.27
   684.7 2211.16   769.8 2253.68   779.7 2254.72   792.8 2262.09     819 2271.63
#Mann= 3 ,-1 , 0
       0     .12       0   419.6    .045       0   445.7     .12       0
Bank Sta=419.6,445.7
XS Rating Curve= 0 ,0
Exp/Cntr=0.3,0.1