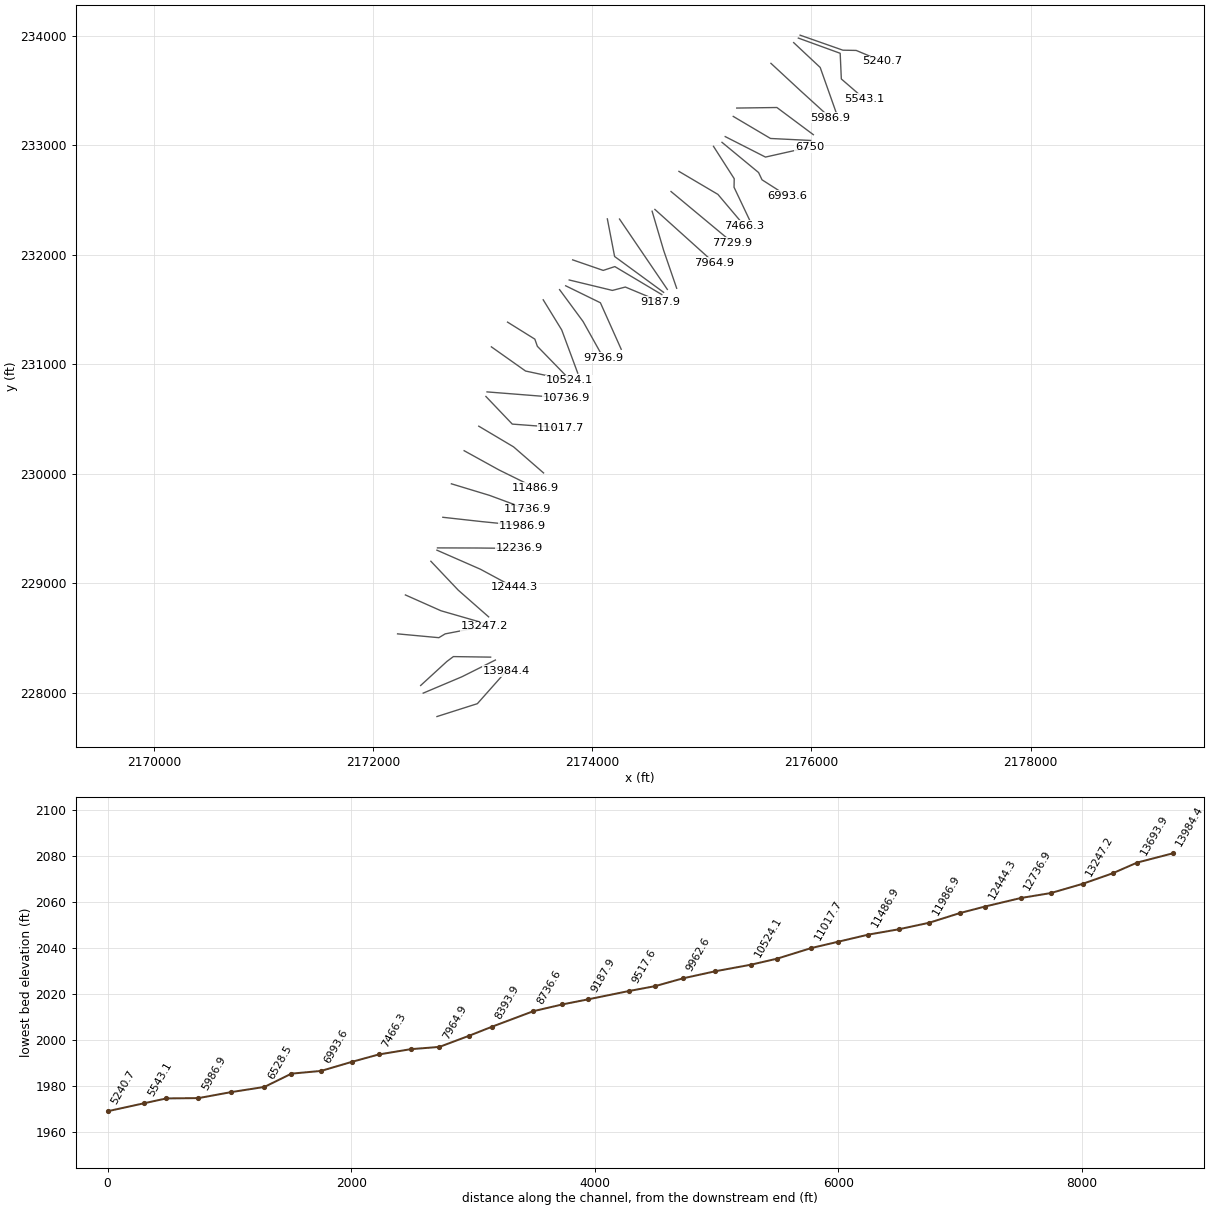
HEC-RAS study BACKCK2.prj: BACKCK2

--- BACKCK2.g01 (geometry) --- (continued)

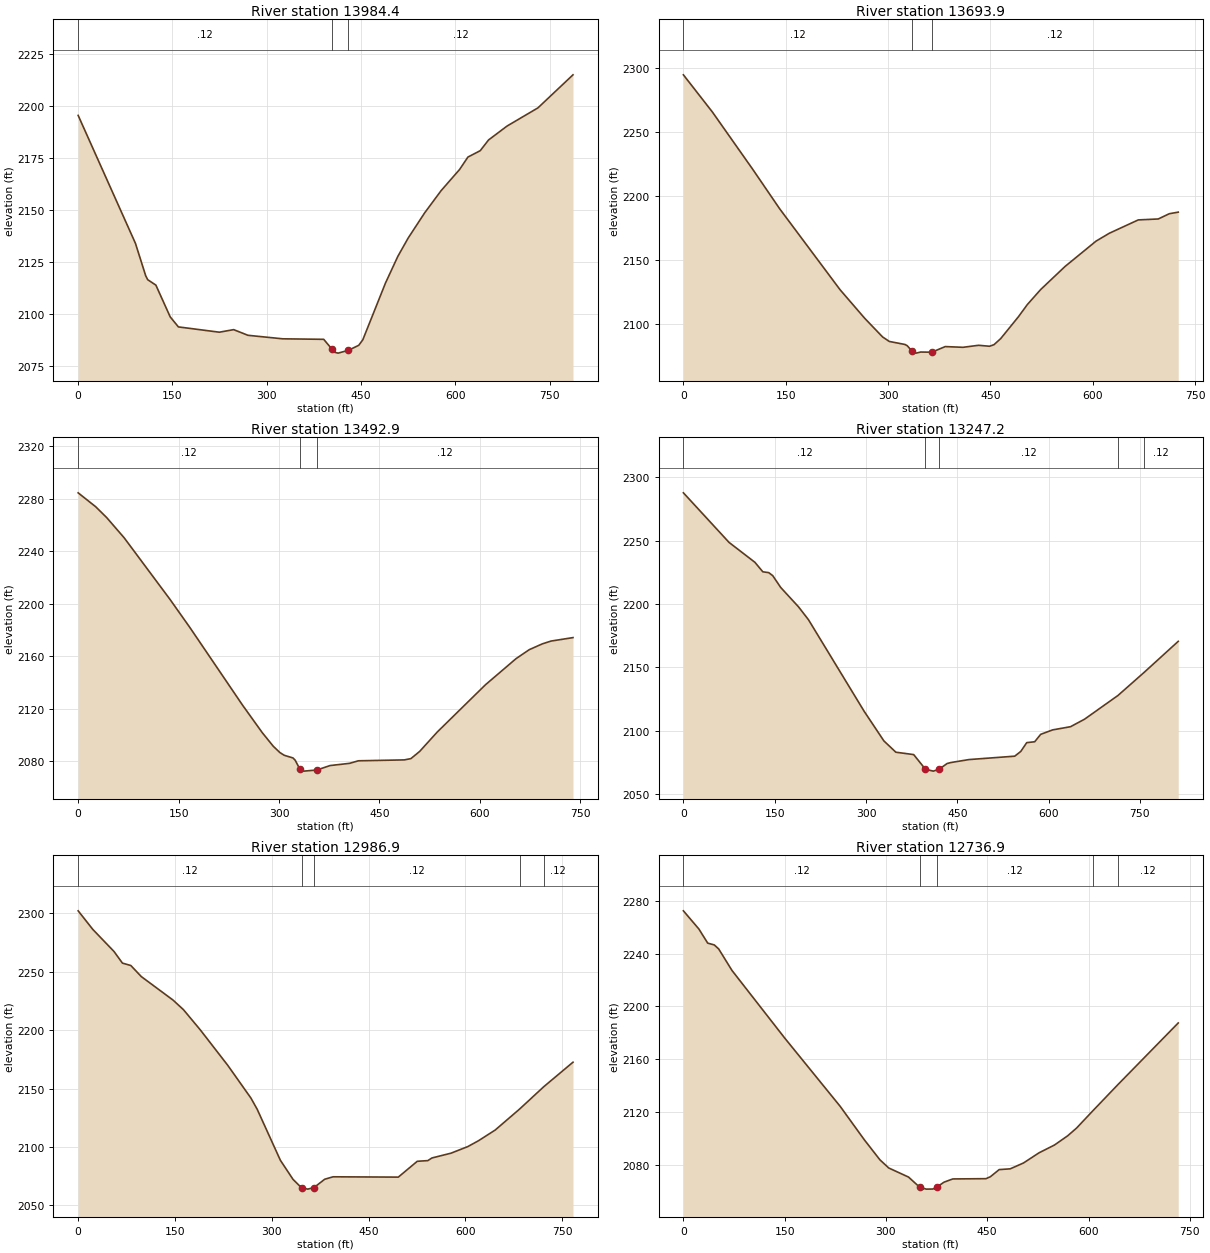
Type RM Length L Ch R = 1 ,13984.4 ,303.7,290.5,273.5
XS GIS Cut Line= 3
     2172580.631      227784.044     2172949.536      227901.604
     2173215.073      228200.334
#Sta/Elev= 30
       0 2195.31    91.1 2133.88   107.4 2118.33   110.6 2116.42   123.6 2113.82
   146.4 2098.56   159.4 2093.75   224.5 2091.21   247.3 2092.44     270 2089.72
   325.4 2088.03   390.5 2087.79   403.6 2083.07   406.8 2081.64   413.4 2081.16
   429.8 2082.52   446.2 2084.92   452.7 2087.58   488.7  2114.8   508.4 2127.64
   524.8 2136.42     551  2148.5   577.2 2159.18   606.7 2169.39   619.8  2175.3
   639.4 2178.36   652.6 2183.51     682 2190.18   731.2 2198.93   786.9 2214.79
#Mann= 3 ,-1 , 0
       0     .12       0   403.6    .045       0   429.8     .12       0
Bank Sta=403.6,429.8
XS Rating Curve= 0 ,0
Exp/Cntr=0.3,0.1

Type RM Length L Ch R = 1 ,13693.9 ,189.6,201,210
XS GIS Cut Line= 3
     2172454.973      227997.861     2172808.469      228147.226
      2173113.92      228299.945
#Sta/Elev= 30
       0  2294.8    42.6 2265.64   101.7 2220.85     141 2190.12   229.6 2126.77
   265.7 2104.44   291.9 2089.85   301.8  2086.3   324.7 2083.95     328 2083.01
   334.6 2079.02   341.1 2077.17   347.7 2078.02   364.1  2077.9   383.8 2082.29
   409.8 2081.72   432.5 2083.29   448.8 2082.55   455.3  2083.8   465.1 2088.55
   491.1 2105.65   504.1 2115.13   523.6 2126.86   559.4 2144.94   604.9 2164.79
   624.4 2170.94   666.7 2181.34     696 2182.08   712.2 2186.18   725.3 2187.42
#Mann= 3 ,-1 , 0
       0     .12       0   334.6    .045       0   364.1     .12       0
Bank Sta=334.6,364.1
XS Rating Curve= 0 ,0
Exp/Cntr=0.3,0.1

Type RM Length L Ch R = 1 ,13492.9 ,258.5,245.7,240.4
XS GIS Cut Line= 4
     2172431.738      228067.565     2172670.722      228286.633
     2172730.468      228331.443     2173070.687      228326.464
#Sta/Elev= 30
       0 2284.65    26.2 2274.04    42.6 2265.79    68.8 2250.32   137.5 2203.21
     167  2181.9   245.6 2122.77   275.1 2101.77   291.4 2091.49   301.3 2086.67
   307.8 2084.59   320.9 2082.55   324.2  2080.8   330.7 2074.45   333.9 2072.77
   337.2 2072.51   356.7 2073.39   376.2 2076.75   405.4 2078.45   418.5 2080.38
   487.2 2081.07     497 2082.04   510.1 2087.54   536.3 2102.28   608.3 2138.31
   654.1 2158.27   673.7 2165.07   693.3 2169.52   706.4 2171.66   739.1 2174.29
#Mann= 3 ,-1 , 0
       0     .12       0   330.7    .045       0   356.7     .12       0
Bank Sta=330.7,356.7
XS Rating Curve= 0 ,0
Exp/Cntr=0.3,0.1

Type RM Length L Ch R = 1 ,13247.2 ,289.6,260.3,228.7
XS GIS Cut Line= 4
     2172220.968      228538.894     2172597.699      228504.042
     2172655.786      228538.894      2173015.92      228608.597
#Sta/Elev= 30
       0 2287.72      75 2248.56   117.4 2232.88   130.5 2225.35   140.2  2224.7
   146.8 2222.29   159.8 2213.01   189.2 2197.64   205.5 2187.49   296.8 2115.31
   329.4 2091.79     349 2082.89   378.3 2081.01   397.7 2069.38   410.6 2067.95
   420.3 2069.53   433.2 2073.95   439.6 2074.75     469 2077.07   544.3 2079.76
   554.2 2083.49     564 2090.44   577.1 2091.15   586.9 2096.99   606.6 2100.52
     636 2103.04     659 2108.96  713.822127.668  756.76 2145.88   812.9 2170.44
#Mann= 5 ,-1 , 0
       0     .12       0   397.7    .045       0   420.3     .12       0
  713.82    .016       0  756.76     .12       0
Bank Sta=397.7,420.3
XS Rating Curve= 0 ,0
Exp/Cntr=0.3,0.1

Type RM Length L Ch R = 1 ,12986.9 ,264.9,250,233
XS GIS Cut Line= 3
     2172292.408      228894.228     2172617.575      228749.662
     2173012.496      228635.886
#Sta/Elev= 30
       0 2301.96    22.8 2286.01    55.5 2267.23    68.6 2257.24    81.6  2255.2
    97.9  2245.7   146.9 2225.68   163.2 2217.41   189.4 2200.05   231.8 2169.85
   267.7 2141.83   277.5 2132.18   313.4 2088.59     333 2072.26   346.1 2065.09
   355.8 2063.94   365.6 2065.32     382 2072.39     395 2074.48   496.1 2074.21
   525.5 2087.75   541.8 2088.32   548.3 2090.59   577.7 2094.67   603.8 2100.32
   620.1 2105.24   646.2 2114.46  684.012132.392  721.42 2151.48   766.8 2172.49
#Mann= 5 ,-1 , 0
       0     .12       0   346.1    .045       0   365.6     .12       0
  684.01    .016       0  721.42     .12       0
Bank Sta=346.1,365.6
XS Rating Curve= 0 ,0
Exp/Cntr=0.3,0.1

Type RM Length L Ch R = 1 ,12736.9 ,276.4,292.6,302.4
XS GIS Cut Line= 3
     2172524.956       229201.74     2172774.579       228938.25
     2173052.434      228694.064
#Sta/Elev= 30
       0 2272.41    22.9 2258.67      36 2247.97    45.8 2246.58    52.3 2243.53
    71.9 2227.31   150.4 2175.87   232.2 2124.42   268.1    2099     291 2083.97
   304.1 2077.77   333.5 2070.86   349.9 2063.23   359.7 2061.75   369.5 2061.82
     376 2063.47   385.9    2067     399 2069.46   448.1 2069.66   454.6 2071.11
   467.7 2076.54   484.1 2077.11   503.7 2081.54   526.6  2089.2   549.6 2095.14
   569.2 2102.13   582.3 2107.96  606.732121.205  643.722140.954   732.9 2187.53
#Mann= 5 ,-1 , 0
       0     .12       0   349.9    .045       0     376     .12       0
  606.73    .016       0  643.72     .12       0
Bank Sta=349.9,376
XS Rating Curve= 0 ,0
Exp/Cntr=0.3,0.1

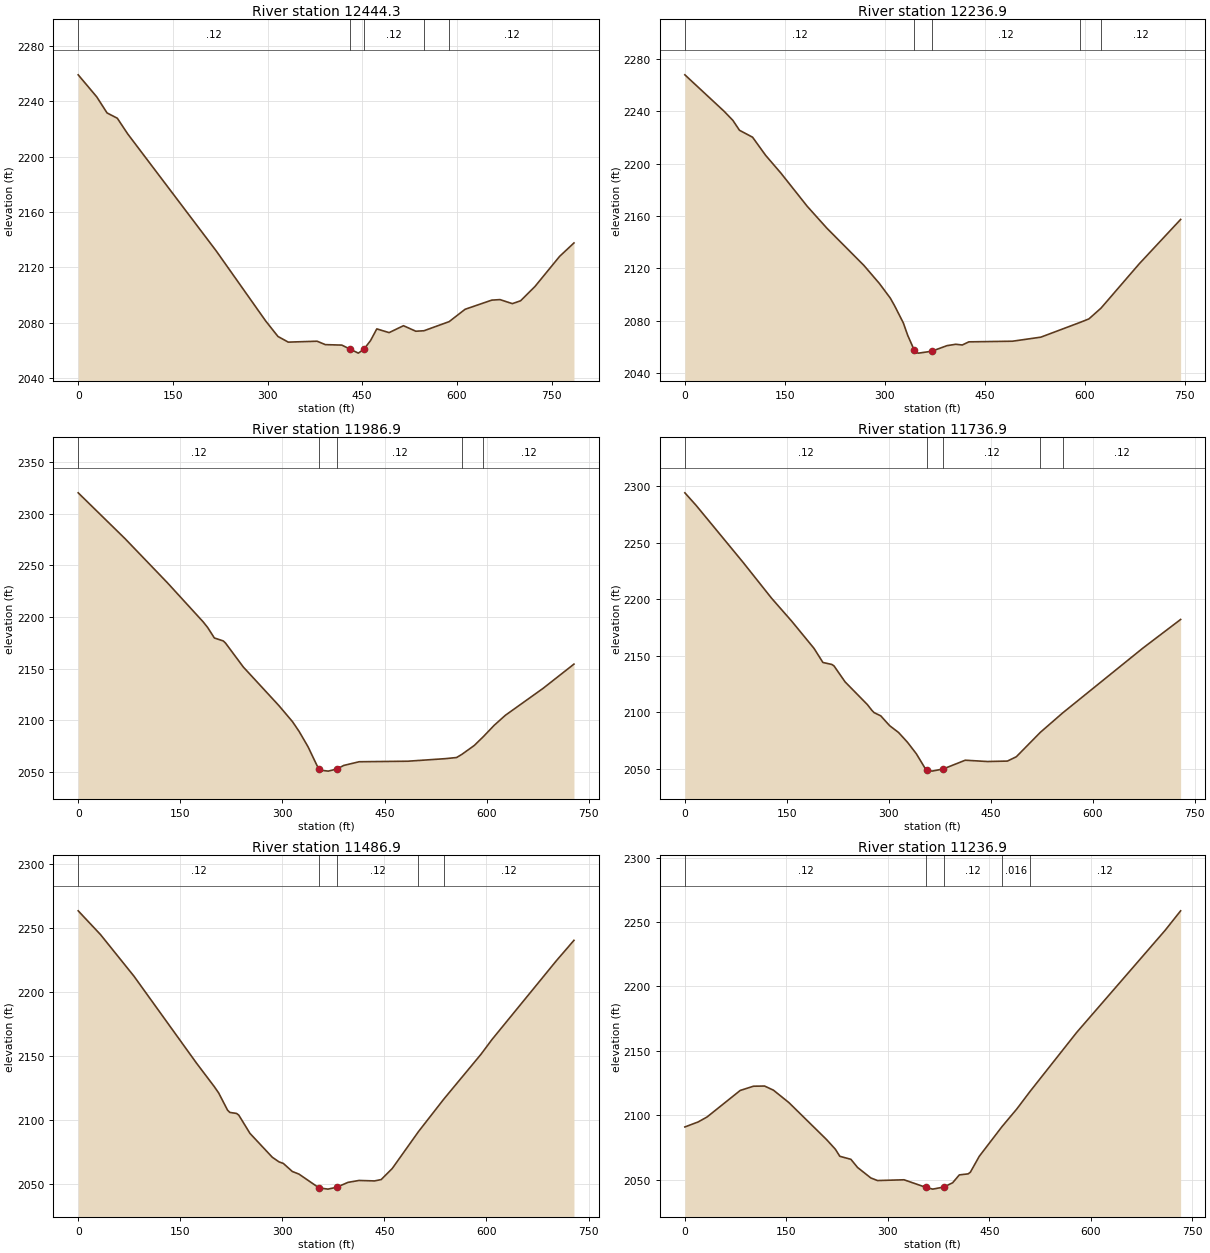
Type RM Length L Ch R = 1 ,12444.3 ,190.5,207.4,225.4
XS GIS Cut Line= 3
     2172580.045      229303.108     2172977.557      229128.881
     2173287.075      228962.345
#Sta/Elev= 30
       0 2259.19    29.4 2243.25    45.7 2231.66      62 2227.81    78.3 2216.58
   218.6 2131.98     297 2081.34   316.5 2070.11   332.8 2066.01   378.5 2066.67
   391.6  2064.2   417.7 2063.86   430.8 2060.93   443.8 2058.06   452.6 2060.83
   463.3 2067.19   473.1 2075.58   492.6 2072.88   515.4 2077.88   534.9 2073.89
  547.872074.235   587.82080.827     613 2089.74   655.3 2096.37   668.3 2096.74
   687.9 2093.83   700.9 2095.88   723.7  2106.2   762.7 2127.95   785.5 2137.69
#Mann= 5 ,-1 , 0
       0     .12       0   430.8    .045       0   452.6     .12       0
  547.87    .016       0   587.8     .12       0
Bank Sta=430.8,452.6
XS Rating Curve= 0 ,0
Exp/Cntr=0.3,0.1

Type RM Length L Ch R = 1 ,12236.9 ,253.6,250,246.2
XS GIS Cut Line= 3
     2172585.299      229323.793     2172945.943      229322.856
     2173329.225      229318.942
#Sta/Elev= 30
       0    2268      59 2240.07    72.1 2233.14      82 2225.59   101.6  2220.3
   121.3 2206.38   144.3 2192.74   183.6 2167.49   213.1 2150.74   268.8  2122.2
   291.8 2108.52   308.2 2097.35   314.8 2091.38   327.9 2078.26   334.4 2068.82
   344.2 2057.54   347.5 2055.53   350.8  2055.2   370.5 2056.65   393.4 2060.92
   406.5 2061.96   416.3 2061.43   426.2 2063.82   491.7 2064.31   534.3 2067.42
  592.842078.637   606.4 2081.39  624.542089.606   681.7 2123.39     744 2157.43
#Mann= 5 ,-1 , 0
       0     .12       0   344.2    .045       0   370.5     .12       0
  592.84    .016       0  624.54     .12       0
Bank Sta=344.2,370.5
XS Rating Curve= 0 ,0
Exp/Cntr=0.3,0.1

Type RM Length L Ch R = 1 ,11986.9 ,256.8,250,240.2
XS GIS Cut Line= 3
     2172634.198      229603.328     2172995.928      229563.136
     2173358.403      229527.246
#Sta/Elev= 30
       0 2320.25    68.9 2275.85   131.2 2233.13   183.6 2195.38   190.2 2189.93
     200 2179.84   213.1 2176.96   216.4  2174.9   242.6 2151.68   295.1 2114.19
   314.8 2098.85   324.6 2089.31   337.7 2074.46   350.8 2056.37   354.1 2053.29
   357.4 2051.84   367.2 2051.02   380.2 2053.12     390 2056.52   412.7 2060.09
   484.3 2060.61   539.6  2063.1   555.8 2064.18  563.562067.238   581.8 2075.85
   595.22084.448   611.1 2095.39   627.4 2105.02   682.7 2131.02   728.2 2154.54
#Mann= 5 ,-1 , 0
       0     .12       0   354.1    .045       0   380.2     .12       0
  563.56    .016       0   595.2     .12       0
Bank Sta=354.1,380.2
XS Rating Curve= 0 ,0
Exp/Cntr=0.3,0.1

Type RM Length L Ch R = 1 ,11736.9 ,257.6,250,246
XS GIS Cut Line= 3
     2172712.189      229908.965      2173060.07      229803.436
     2173403.277      229676.661
#Sta/Elev= 30
       0 2294.16    16.4 2283.18    85.2 2233.04   127.7 2200.91   157.2  2180.7
     190 2156.69   203.1 2144.22   216.2 2142.47   219.4 2141.19   235.8 2127.02
   268.6 2106.94   275.1 2101.94   278.4 2099.89   288.2 2097.05   301.3 2088.34
   314.4 2082.33   327.5 2073.72   340.6 2063.48   353.7 2050.45     356  2049.6
   363.5 2048.18   379.9 2050.05   412.5 2057.82   445.2 2056.67   474.6 2057.06
   487.7  2060.9  522.982082.448  555.892099.635   673.9 2156.92   729.4 2182.23
#Mann= 5 ,-1 , 0
       0     .12       0     356    .045       0   379.9     .12       0
  522.98    .016       0  555.89     .12       0
Bank Sta=356,379.9
XS Rating Curve= 0 ,0
Exp/Cntr=0.3,0.1

Type RM Length L Ch R = 1 ,11486.9 ,251.2,250,240.3
XS GIS Cut Line= 3
     2172828.708      230211.136     2173147.296      230035.364
     2173474.545      229874.172
#Sta/Elev= 30
       0  2263.6    32.8    2245      82 2212.43   173.7 2144.56     200 2126.05
   206.5 2121.05   219.6 2107.56   222.9 2105.87   232.7 2105.08     236 2103.76
   252.4  2089.5   285.2 2070.83     295 2067.22   301.6 2065.92   314.7 2059.66
   324.5  2057.6     354 2046.83   367.1 2045.86   380.2 2047.37   396.4 2051.14
   412.7 2052.64   435.5 2052.28   445.3 2053.35   461.6 2062.04  499.942090.759
  537.472116.396   591.9 2151.32   608.1 2162.89   702.6 2224.46   728.6 2240.52
#Mann= 5 ,-1 , 0
       0     .12       0     354    .045       0   380.2     .12       0
  499.94    .016       0  537.47     .12       0
Bank Sta=354,380.2
XS Rating Curve= 0 ,0
Exp/Cntr=0.3,0.1

Type RM Length L Ch R = 1 ,11236.9 ,201.8,219.2,243.2
XS GIS Cut Line= 3
     2172962.176      230435.127     2173279.961      230246.271
     2173553.883      230008.078
#Sta/Elev= 30
       0 2090.98    19.6 2094.86    32.7 2098.69    81.8 2119.31   101.4  2122.6
   117.8 2122.73   130.9 2119.53   153.8 2109.86   209.4  2081.2   222.4 2073.71
     229 2068.22   245.4 2065.86   255.2 2059.55   274.8 2051.43   284.6 2049.39
   323.9 2049.98   356.6 2044.03   366.4 2042.73   382.8 2044.38   395.8 2047.68
   405.6 2053.77   418.7 2054.57     422 2055.92   435.1  2068.2   468.62091.167
   490.7 2105.01  509.82 2118.32     579 2164.29   709.8 2243.58   732.7 2258.71
#Mann= 5 ,-1 , 0
       0     .12       0   356.6    .045       0   382.8     .12       0
   468.6    .016       0  509.82     .12       0
Bank Sta=356.6,382.8
XS Rating Curve= 0 ,0
Exp/Cntr=0.3,0.1

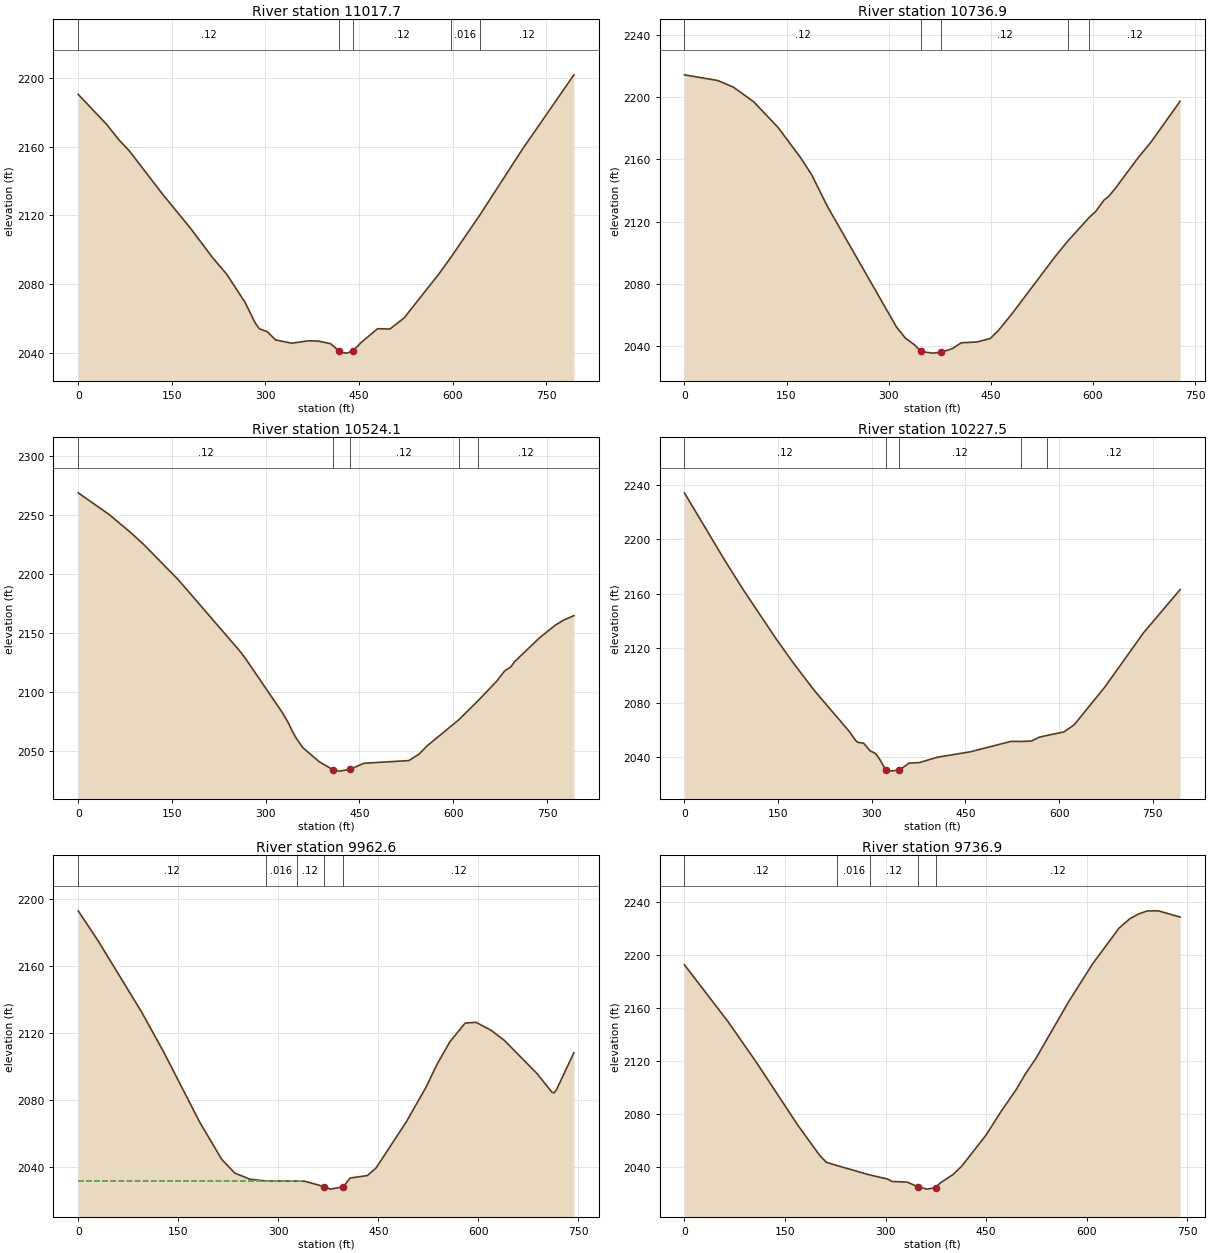
Type RM Length L Ch R = 1 ,11017.7 ,280.8,280.8,280.3
XS GIS Cut Line= 3
     2173027.538      230706.341     2173268.181      230454.081
     2173712.318      230420.931
#Sta/Elev= 30
       0 2190.37    45.6 2172.91    65.2 2163.95    81.5 2157.71   136.8 2131.63
   179.2 2112.89     215 2095.62   237.8 2085.89   267.2 2069.58   283.5 2057.56
     290  2054.2     303 2052.44     316  2047.7   342.1 2045.77   368.3 2047.17
   384.6 2047.02   404.3 2045.49   417.4 2041.35   420.7 2040.42   430.5 2040.01
   440.3 2041.38   453.4 2046.24   479.6  2054.2   499.3 2054.02   522.2  2060.5
   577.9  2086.1  596.622095.475  642.792119.969   712.1 2158.79     794 2201.72
#Mann= 5 ,-1 , 0
       0     .12       0   417.4    .045       0   440.3     .12       0
  596.62    .016       0  642.79     .12       0
Bank Sta=417.4,440.3
XS Rating Curve= 0 ,0
Exp/Cntr=0.3,0.1

Type RM Length L Ch R = 1 ,10736.9 ,217.8,212.8,207.8
XS GIS Cut Line= 3
     2173037.674      230748.117     2173400.545      230719.469
     2173763.416      230690.821
#Sta/Elev= 30
       0 2214.42    49.2 2210.75    72.1 2206.45   101.7 2197.14   137.7 2180.48
   170.5 2161.24   186.9 2150.14   209.9 2129.88   311.5 2052.17   324.6 2045.02
   337.8 2040.79   347.6 2036.47     364 2035.39   377.1 2035.91   393.5  2038.3
   406.6 2042.05   429.6 2042.55   449.3 2044.83   462.4 2050.56     482 2061.24
   544.4 2097.47  563.532107.726  594.792122.814   603.4 2126.19   616.5 2133.94
   623.1 2136.19   632.9 2141.43   665.7 2160.71   685.4 2171.26     728 2197.45
#Mann= 5 ,-1 , 0
       0     .12       0   347.6    .045       0   377.1     .12       0
  563.53    .016       0  594.79     .12       0
Bank Sta=347.6,377.1
XS Rating Curve= 0 ,0
Exp/Cntr=0.3,0.1

Type RM Length L Ch R = 1 ,10524.1 ,330.9,296.6,259
XS GIS Cut Line= 3
     2173077.326      231159.414     2173389.332      230938.686
     2173790.957      230852.387
#Sta/Elev= 30
       0 2268.57      49 2250.42    84.9 2234.49   104.5 2224.96   160.1 2194.98
   258.1 2134.81   267.9 2128.01   326.7 2082.29   336.5 2073.41     343  2066.1
   349.5 2060.11   359.3 2052.72   385.4 2040.83   408.3 2033.73     418 2032.79
   434.4 2034.24   457.2 2039.46   528.9 2041.73   545.2 2047.18   558.2 2054.21
  608.592076.166   640.22092.721   669.1 2108.74   682.1 2117.62   691.9 2121.01
   698.4 2125.66   737.6 2145.55   763.6  2156.6   776.7 2160.75     793 2164.51
#Mann= 5 ,-1 , 0
       0     .12       0   408.3    .045       0   434.4     .12       0
  608.59    .016       0   640.2     .12       0
Bank Sta=408.3,434.4
XS Rating Curve= 0 ,0
Exp/Cntr=0.3,0.1

Type RM Length L Ch R = 1 ,10227.5 ,270.3,264.9,261.9
XS GIS Cut Line= 4
     2173225.031      231385.121     2173474.258        231229.8
     2173497.207      231164.393     2173797.596      230855.706
#Sta/Elev= 30
       0 2233.97    65.3 2183.97    94.6 2162.67   146.8 2126.99   172.9 2110.15
   208.8 2088.57   264.3 2058.85   274.1 2052.44   277.4 2051.08   287.1 2050.35
   296.8 2044.98   306.3 2042.67   312.6 2038.71     322    2031   328.3  2029.9
   344.1 2030.67   359.8 2035.76     376 2036.16   405.4 2040.12   457.6 2044.05
   522.9 2051.71  538.352051.659   555.5 2051.95   568.6 2054.84  580.642056.083
   607.7 2058.65     624 2063.83     673 2091.44     735 2131.25   793.7    2163
#Mann= 5 ,-1 , 0
       0     .12       0     322    .045       0   344.1     .12       0
  538.35    .016       0  580.64     .12       0
Bank Sta=322,344.1
XS Rating Curve= 0 ,0
Exp/Cntr=0.3,0.1

Type RM Length L Ch R = 1 ,9962.6  ,213.6,225.7,231.4
XS GIS Cut Line= 3
     2173550.629      231588.843     2173719.594      231313.758
     2173865.815      230919.519
#Sta/Elev= 30
       0 2192.99    29.4 2175.38    94.6 2132.89   127.2 2109.45   182.6 2066.51
   215.2 2044.62   234.8 2036.42   257.6 2032.73  281.22 2031.69  327.382031.613
   339.1 2031.59   368.5 2028.36   378.2 2026.82   397.8 2028.24   407.6 2033.43
   433.7 2034.93   446.7 2039.46   492.3  2067.2   521.7  2087.8     538 2101.28
   557.5  2114.9   580.3    2126   596.6 2126.41   619.4  2121.6     639 2115.62
   687.9 2095.87   710.7 2084.56     714  2084.4   717.2 2086.19   743.3  2108.3
#Mann= 5 ,-1 , 0
       0     .12       0  281.22    .016       0  327.38     .12       0
   368.5    .045       0   397.8     .12       0
#XS Ineff= 2 , 0
          336.12 2031.79
Permanent Ineff=
       F       F
Bank Sta=368.5,397.8
XS Rating Curve= 0 ,0
Exp/Cntr=0.3,0.1

Type RM Length L Ch R = 1 ,9736.9  ,227.1,219.3,215.8
XS GIS Cut Line= 3
     2173700.158      231681.662     2173914.672      231390.536
     2174098.965      231061.109
#Sta/Elev= 30
       0 2192.47    65.2 2149.54   107.5 2118.84   169.4  2071.4     202 2048.68
   211.8 2043.63  227.632041.208  277.222034.034     303 2031.06   309.5 2029.24
   332.3 2028.75   348.6 2025.16   361.6 2023.47   374.6 2024.66   381.2 2028.03
   400.7 2034.53   413.7 2040.88   449.5 2064.02   472.3 2082.07     495 2098.69
   508.1 2109.96   524.3  2122.1   573.1 2164.81   608.9 2193.33     648 2220.03
   664.2 2227.18   677.3 2230.78   690.3 2233.01   706.6 2233.09   739.1  2228.4
#Mann= 5 ,-1 , 0
       0     .12       0  227.63    .016       0  277.22     .12       0
   348.6    .045       0   374.6     .12       0
Bank Sta=348.6,374.6
XS Rating Curve= 0 ,0
Exp/Cntr=0.3,0.1

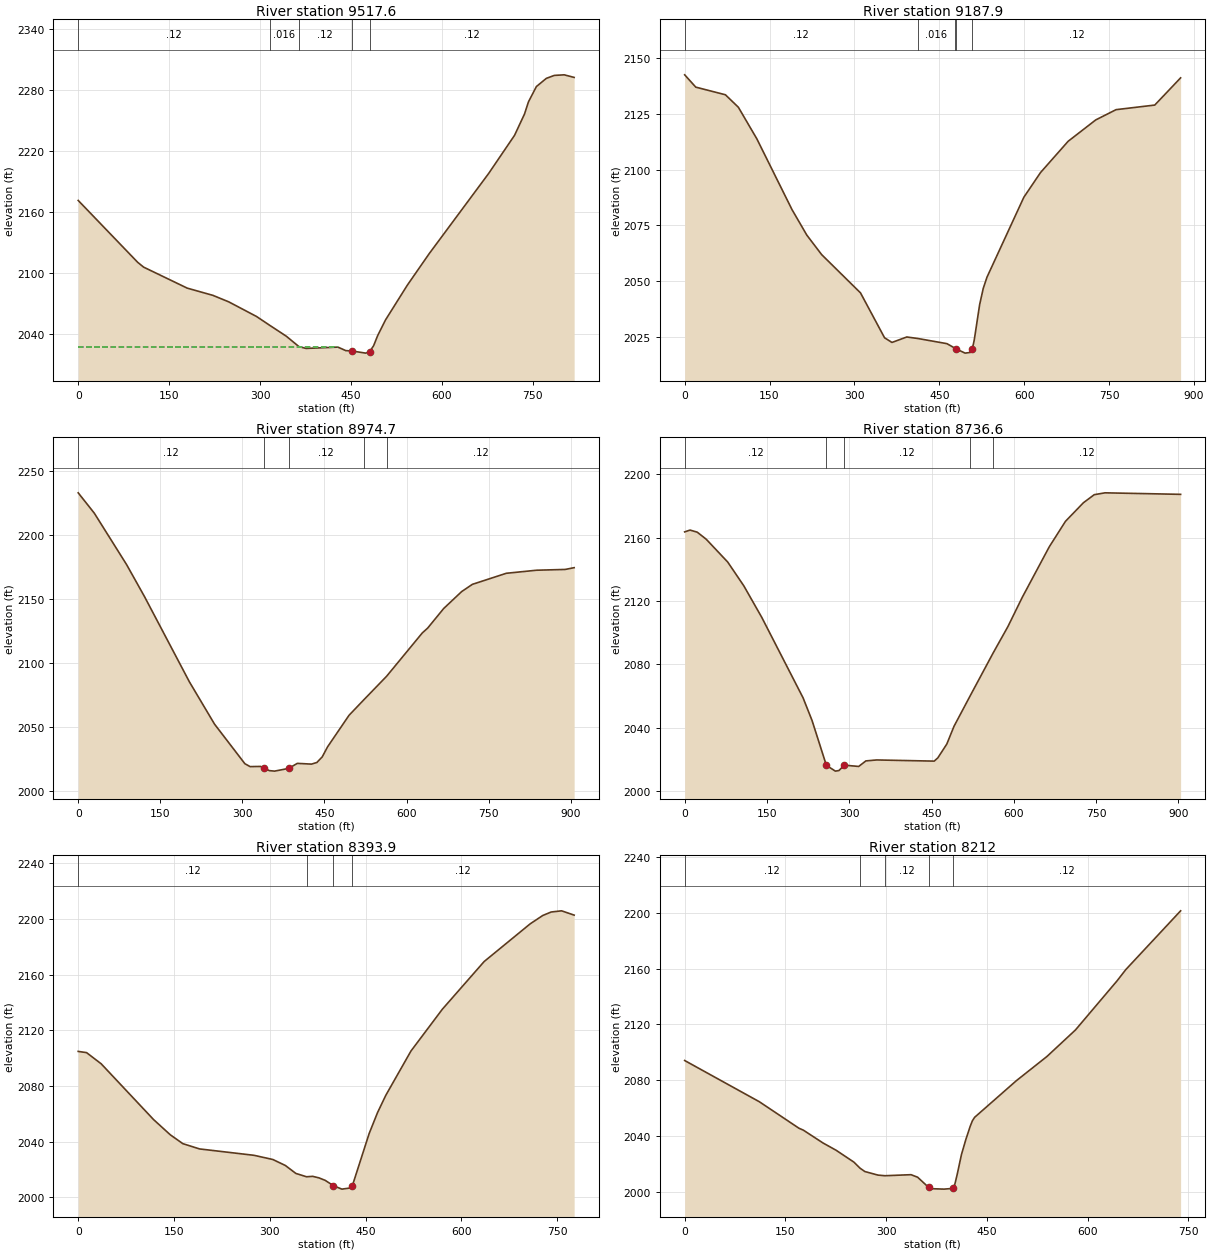
Type RM Length L Ch R = 1 ,9517.6  ,275.2,329.7,376.6
XS GIS Cut Line= 3
      2173755.69      231716.916     2174072.844      231561.772
     2174262.792      231137.216
#Sta/Elev= 30
       0 2171.61    98.1 2110.71   107.9 2105.97   179.8  2085.3   222.3 2078.16
   248.4 2071.77   294.2 2057.37  316.072048.638   343.3 2037.96  364.11 2027.74
     376 2025.92   428.4 2027.23   441.5 2023.76   451.3 2023.44   474.3  2021.3
   480.8 2022.73   487.4 2028.65   493.9 2038.37     507 2053.98     543 2088.22
   579.1 2119.26   677.3 2198.29   719.9 2235.74   736.3  2256.7   742.8 2268.64
   755.9 2283.73   772.3 2291.78   785.4  2294.7   801.8 2295.28   818.2 2292.73
#Mann= 5 ,-1 , 0
       0     .12       0  316.07    .016       0  364.11     .12       0
   451.3    .045       0   480.8     .12       0
#XS Ineff= 2 , 0
          427.99 2027.22
Permanent Ineff=
       F       F
Bank Sta=451.3,480.8
XS Rating Curve= 0 ,0
Exp/Cntr=0.3,0.1

Type RM Length L Ch R = 1 ,9187.9  ,211.4,213.2,221.8
XS GIS Cut Line= 4
     2173787.924      231769.869     2174182.219      231674.619
     2174300.457      231705.425     2174622.304      231571.123
#Sta/Elev= 30
       0 2142.54    19.6 2137.02      72  2133.6    94.9    2128   127.6 2113.82
   189.7 2082.11   215.9 2070.66   242.1 2061.92   310.8 2044.75   353.3 2024.63
   366.4 2022.53   392.6 2024.98  412.252024.293   463.5 2021.99  477.662019.975
   479.6 2019.66   495.7 2017.74   505.3 2018.07   508.5  2019.7   511.8 2023.56
   521.4 2039.54   527.8 2046.85   534.3 2051.77   599.5 2087.64   628.9 2098.69
   677.8 2112.74   726.6 2122.32   762.5 2126.92   830.9 2128.98   876.6 2141.18
#Mann= 5 ,-1 , 0
       0     .12       0  412.25    .016       0  477.66     .12       0
   479.6    .045       0   508.5     .12       0
Bank Sta=479.6,508.5
XS Rating Curve= 0 ,0
Exp/Cntr=0.3,0.1

Type RM Length L Ch R = 1 ,8974.7  ,301.7,238.1,174
XS GIS Cut Line= 4
     2173819.553      231953.601     2174098.367      231857.344
     2174204.582      231892.196     2174633.608      231636.424
#Sta/Elev= 30
       0 2232.88    29.5 2216.93    88.5 2176.76   121.3 2151.69   203.2 2085.23
   249.1 2052.21   304.5 2021.32   314.1 2019.04   333.3 2019.18   339.7  2017.9
   349.3  2015.9   358.8 2015.51   384.4 2017.62   400.4 2021.57   426.3 2020.99
   436.1 2022.27   445.9 2026.66   455.7 2034.52   494.9 2059.14  522.082071.296
  563.552089.624   628.7 2123.43   638.5  2127.2   667.9 2142.56   700.6 2155.72
   720.2 2161.39   782.2 2170.04   837.7 2172.43   889.9 2173.04   906.2 2174.42
#Mann= 5 ,-1 , 0
       0     .12       0   339.7    .045       0   384.4     .12       0
  522.08    .016       0  563.55     .12       0
Bank Sta=339.7,384.4
XS Rating Curve= 0 ,0
Exp/Cntr=0.3,0.1

Type RM Length L Ch R = 1 ,8736.6  ,326.9,342.7,357.3
XS GIS Cut Line= 3
     2174136.156      232327.778      2174202.54      231984.239
     2174649.793      231657.205
#Sta/Elev= 30
       0 2163.72     9.8 2164.85    22.9 2163.54    39.2  2159.1    78.5 2144.64
   107.9 2129.58   140.6 2109.66   215.8 2058.89   232.2 2044.55   258.3 2016.22
   274.7 2012.58   281.2 2012.95     291 2016.34   317.2 2015.54   330.3 2019.03
   349.9 2019.64   454.8  2018.9   461.4 2020.93   477.8 2029.68   490.9 2040.88
  520.782060.397  562.072087.094   589.2  2103.9   615.4  2122.4   664.6  2154.3
   694.1 2170.38   726.9 2182.16   746.6 2187.22   766.3 2188.39     904 2187.43
#Mann= 5 ,-1 , 0
       0     .12       0   258.3    .045       0     291     .12       0
  520.78    .016       0  562.07     .12       0
Bank Sta=258.3,291
XS Rating Curve= 0 ,0
Exp/Cntr=0.3,0.1

Type RM Length L Ch R = 1 ,8393.9  ,193,182,171.6
XS GIS Cut Line= 2
     2174247.349      232326.118     2174683.826       231683.85
#Sta/Elev= 30
       0 2104.83    13.1 2103.94      36  2095.9     118 2055.79   144.2 2044.83
   163.8 2038.48     190 2034.67   275.2 2030.09   304.7 2027.08   324.4 2022.75
   340.8 2017.05  357.532014.652     367 2014.96   376.8 2013.88   386.6 2012.09
   399.7 2008.21   412.8 2005.76     426 2006.59   429.2 2008.13   455.4 2045.57
   468.6 2060.76   481.6 2073.24     521 2105.11   570.1 2135.14   635.6 2169.48
   707.7  2196.6   727.4 2202.61   740.5  2205.1   756.9 2205.95   776.5 2202.86
#Mann= 4 ,-1 , 0
       0     .12       0  357.53    .016       0   399.7    .045       0
   429.2     .12       0
Bank Sta=399.7,429.2
XS Rating Curve= 0 ,0
Exp/Cntr=0.3,0.1

Type RM Length L Ch R = 1 ,8212    ,226.3,247.1,265.8
XS GIS Cut Line= 3
      2174544.96      232397.691       2174650.3      232039.909
      2174769.08       231694.33
#Sta/Elev= 30
       0 2094.15   111.2 2064.59   170.1 2045.63   176.7 2044.23   206.1    2035
   225.7 2029.76   251.9 2021.34  261.122016.965   268.3 2014.56   287.9    2012
   298.22011.564     337 2012.31   346.8 2010.51   363.2 2003.21   366.4  2002.3
     386 2001.96   399.1 2002.45   402.3 2005.59   405.6 2012.17   412.1 2026.75
   418.6 2037.49   425.2 2047.12   428.4 2050.96   431.7 2053.43   493.7 2079.63
   539.4 2097.05   581.8 2116.04   643.8 2151.27   656.8 2159.33   738.4 2201.45
#Mann= 5 ,-1 , 0
       0     .12       0  261.12    .016       0   298.2     .12       0
   363.2    .045       0   399.1     .12       0
Bank Sta=363.2,399.1
XS Rating Curve= 0 ,0
Exp/Cntr=0.3,0.1

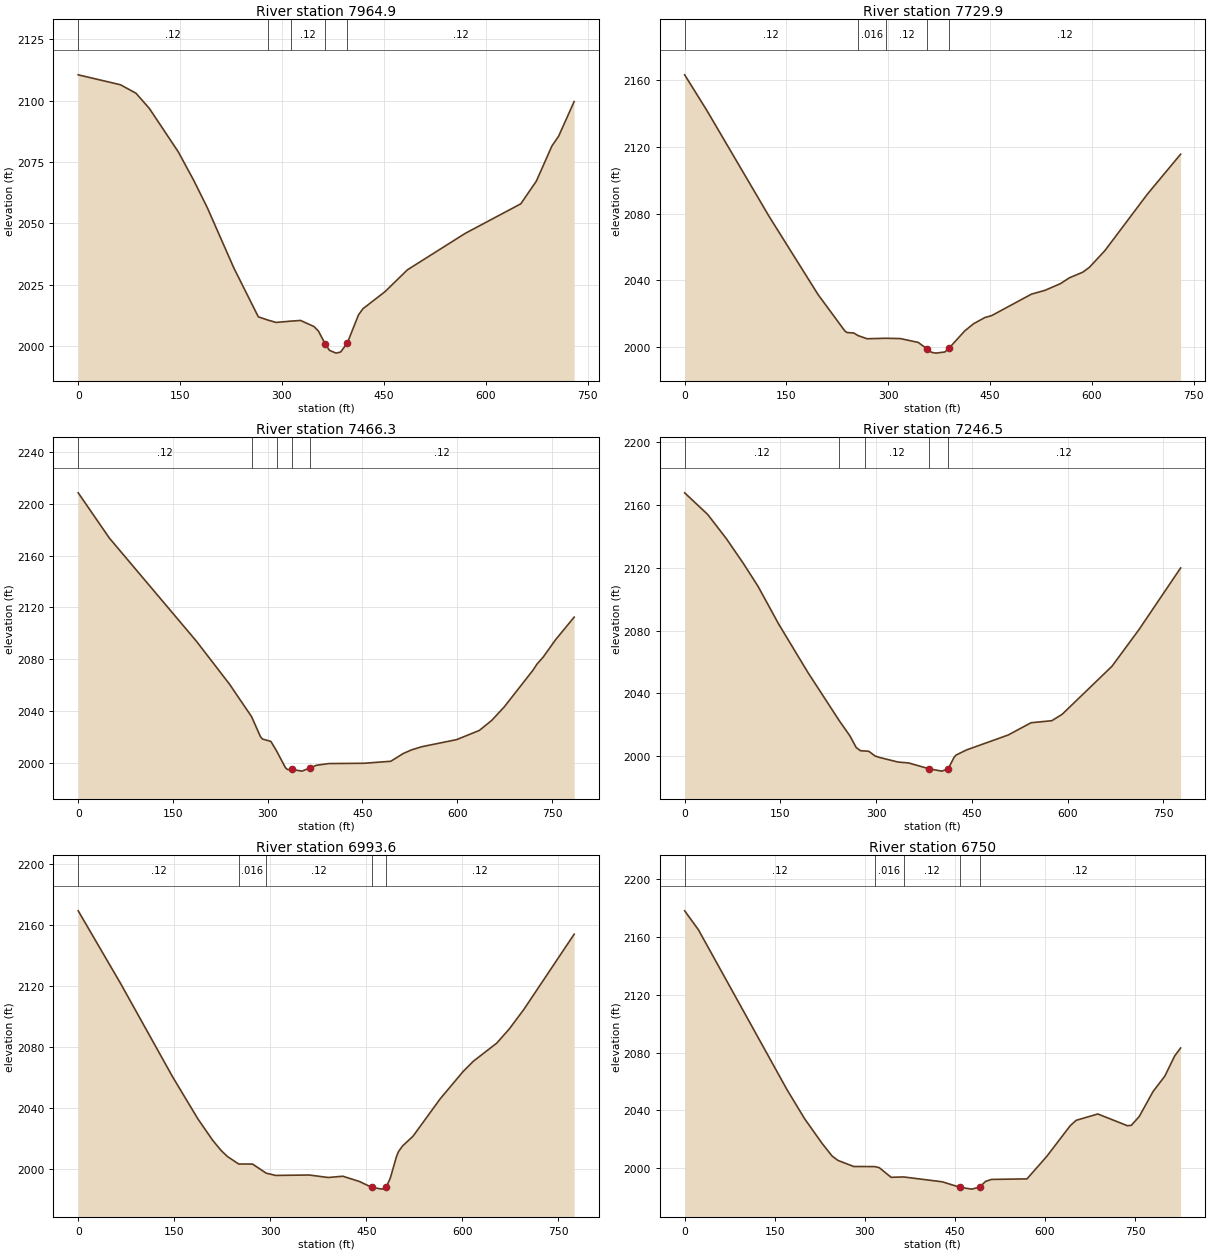
Type RM Length L Ch R = 1 ,7964.9  ,233.5,235,236.5
XS GIS Cut Line= 2
     2174570.342      232414.062     2175113.052      231925.526
#Sta/Elev= 30
       0 2110.53    62.2 2106.48    85.1 2103.02   104.8 2096.81   147.4  2079.1
   170.3 2067.38   189.9 2056.46   229.2 2031.74   265.2 2011.84  279.432010.504
   291.4 2009.56  312.662010.079   327.4 2010.36   347.1 2007.89   353.6 2006.08
   363.5 2000.88     370 1998.16   379.8 1997.04   386.4  1997.5   396.2 2001.16
   412.6 2012.59   419.1 2015.11   451.9 2022.15   484.6 2030.99   569.8 2045.87
   651.6 2057.92   674.5 2067.16   697.5 2081.53   707.3 2085.48   730.2 2099.62
#Mann= 5 ,-1 , 0
       0     .12       0  279.43    .016       0  312.66     .12       0
   363.5    .045       0   396.2     .12       0
Bank Sta=363.5,396.2
XS Rating Curve= 0 ,0
Exp/Cntr=0.3,0.1

Type RM Length L Ch R = 1 ,7729.9  ,257.5,263.6,269.6
XS GIS Cut Line= 2
     2174717.554      232577.637      2175279.49      232110.367
#Sta/Elev= 30
       0 2163.38    32.8 2141.89   124.5  2078.2   196.6 2031.25     236 2009.41
   239.2 2008.44   249.1 2008.17  255.472006.614   268.7 2004.71   296.32004.994
   317.9  2004.8   344.1 2002.51   357.2 1998.61   363.8 1996.55   370.3 1996.06
   383.4 1996.75     390 1999.26   412.9  2009.5     426 2013.81   442.4 2017.45
   452.3 2018.61   511.2 2031.56   530.9  2033.8   553.9 2037.89     567 2041.36
   586.6 2044.71   596.5 2047.69   619.4 2057.78   681.7 2091.58   730.8 2115.66
#Mann= 5 ,-1 , 0
       0     .12       0  255.47    .016       0   296.3     .12       0
   357.2    .045       0     390     .12       0
Bank Sta=357.2,390
XS Rating Curve= 0 ,0
Exp/Cntr=0.3,0.1

Type RM Length L Ch R = 1 ,7466.3  ,259.8,219.8,185
XS GIS Cut Line= 3
     2174789.858      232761.424      2175145.76      232551.355
      2175385.67      232267.335
#Sta/Elev= 30
       0  2208.4    49.2 2173.58     187 2094.04   239.4  2060.9  274.362035.844
   288.6 2020.26   291.9 2018.46     305 2016.68  314.412008.979     328 1996.45
   331.3 1994.98   337.8 1995.06   354.2 1993.75   367.4 1996.32   377.2 1998.27
   396.9 1999.59   452.4 1999.81   494.8 2001.35   514.4 2007.29   527.4 2010.09
   543.7 2012.56   599.2 2018.06     635 2025.15   654.6 2032.88   674.2 2043.15
   719.8 2071.51   726.4 2076.39   736.1 2081.72   755.7  2095.1   785.1 2112.52
#Mann= 5 ,-1 , 0
       0     .12       0  274.36    .016       0  314.41     .12       0
   337.8    .045       0   367.4     .12       0
Bank Sta=337.8,367.4
XS Rating Curve= 0 ,0
Exp/Cntr=0.3,0.1

Type RM Length L Ch R = 1 ,7246.5  ,233.2,252.9,264.9
XS GIS Cut Line= 4
     2175105.366      232989.961     2175294.562      232694.551
     2175292.902       232616.55     2175442.276      232301.859
#Sta/Elev= 30
       0 2167.59    36.1 2153.82    65.6 2138.28    91.8 2122.78   114.8 2108.23
   147.5 2083.97   193.4 2053.14  242.192022.692     259 2012.95   268.8 2005.58
   275.4 2003.54  282.592003.352   288.5 2003.18   298.4 2000.18   304.9 1999.28
   334.4 1996.33   350.8 1995.76   383.3 1992.02   402.8 1990.55   412.6 1991.76
   422.3  1999.4   425.6 2000.84   441.8 2004.05     507 2013.53   542.8 2021.33
   575.3 2022.62   591.6 2026.71   669.7 2057.29     712 2080.61   777.2 2119.81
#Mann= 5 ,-1 , 0
       0     .12       0  242.19    .016       0  282.59     .12       0
   383.3    .045       0   412.6     .12       0
Bank Sta=383.3,412.6
XS Rating Curve= 0 ,0
Exp/Cntr=0.3,0.1

Type RM Length L Ch R = 1 ,6993.6  ,194.5,243.6,294.2
XS GIS Cut Line= 4
     2175182.962      233026.593     2175516.949      232750.978
     2175548.362      232684.625     2175774.188      232540.208
#Sta/Elev= 30
       0  2169.3    65.6 2122.05   147.6  2060.2     187 2032.66     210 2018.68
   223.1 2012.02   232.9 2008.07  250.552003.107   272.3 2003.06  293.611997.078
   308.4  1995.6   360.8 1995.88   390.4 1994.24   413.3 1995.08   439.4 1991.59
   458.2  1987.8   474.5 1986.61   480.9 1987.88   487.3 1993.74   496.9 2007.78
     500 2011.09   506.4  2014.9   522.8 2021.31   565.3  2045.9   601.2 2063.88
   617.6 2070.74   653.5 2082.41   673.2 2091.77     696  2104.6   774.5 2153.94
#Mann= 5 ,-1 , 0
       0     .12       0  250.55    .016       0  293.61     .12       0
   458.2    .045       0   480.9     .12       0
Bank Sta=458.2,480.9
XS Rating Curve= 0 ,0
Exp/Cntr=0.3,0.1

Type RM Length L Ch R = 1 ,6750    ,250.8,221.5,189.3
XS GIS Cut Line= 3
     2175212.379      233079.036     2175580.014      232892.044
     2175983.184      232982.658
#Sta/Elev= 30
       0 2178.18    22.9 2165.06   170.2 2054.45   199.7 2034.17   229.1 2016.92
   245.5 2008.32   255.3 2005.29   281.5 2001.09  316.51 2001.03   324.1 2000.25
   343.7 1993.61  364.621993.851   428.9 1990.49   458.4 1986.67     478 1985.42
   491.2 1986.85     501  1990.8   510.8 1992.15   569.9 1992.51   602.7 2008.02
     642 2029.41   651.9  2033.1   687.9 2037.47   737.1 2029.34   743.7 2029.62
   756.8 2035.73   779.8 2053.01   799.4 2063.68   815.8 2077.66   825.7 2083.18
#Mann= 5 ,-1 , 0
       0     .12       0  316.51    .016       0  364.62     .12       0
   458.4    .045       0   491.2     .12       0
Bank Sta=458.4,491.2
XS Rating Curve= 0 ,0
Exp/Cntr=0.3,0.1

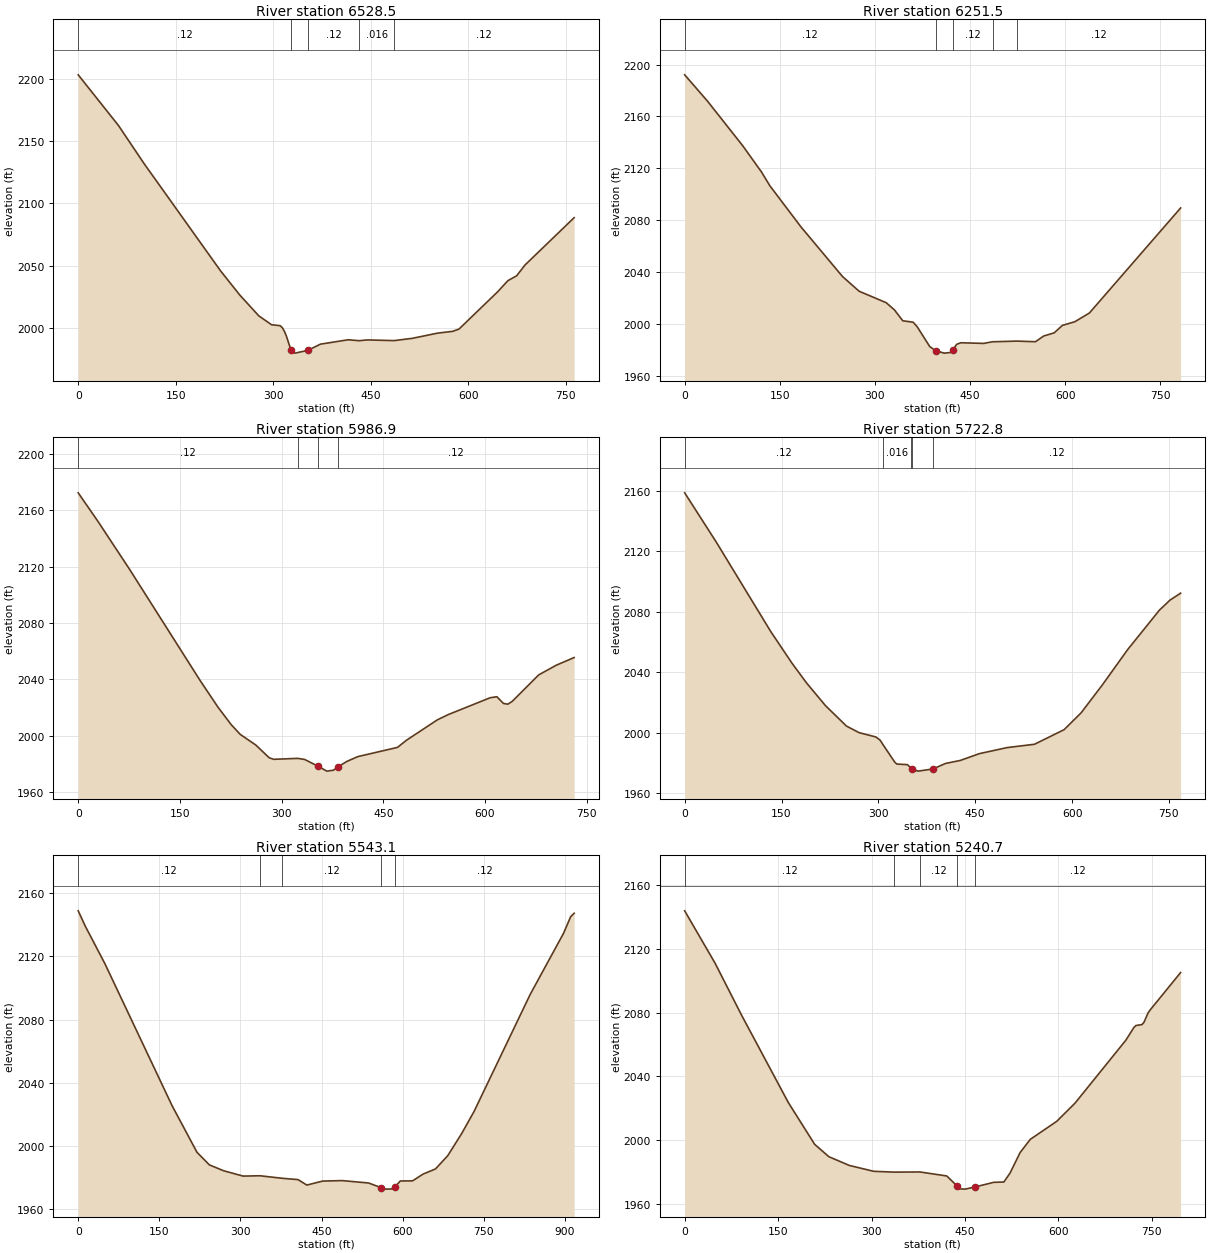
Type RM Length L Ch R = 1 ,6528.5  ,281.4,277,270.9
XS GIS Cut Line= 3
     2175285.662      233263.305      2175625.94      233061.916
     2175992.762      233043.838
#Sta/Elev= 30
       0 2203.43    62.1 2162.56   101.3 2132.05   218.9 2045.83   248.4 2026.43
   277.8 2009.59   297.4 2002.46   310.4 2001.73   313.7 2000.27     317  1997.3
   320.2 1993.29   326.8 1982.75   327.5 1982.16     330 1980.07   333.3 1979.65
   352.9 1981.83   372.5 1986.86   415.1 1990.39  432.051989.645   444.6 1990.26
  485.811989.722   513.5 1991.51   552.8 1995.74   575.8 1997.16   585.6    1999
   644.6 2028.74     661 2038.01   674.1 2041.76   687.2 2050.55   762.7 2088.56
#Mann= 5 ,-1 , 0
       0     .12       0   327.5    .045       0   352.9     .12       0
  432.05    .016       0  485.81     .12       0
Bank Sta=327.5,352.9
XS Rating Curve= 0 ,0
Exp/Cntr=0.3,0.1

Type RM Length L Ch R = 1 ,6251.5  ,267.9,264.7,261.5
XS GIS Cut Line= 3
     2175317.414      233339.603     2175684.187      233344.582
      2176017.05      233096.475
#Sta/Elev= 30
       0 2192.05      36 2171.75    91.7 2137.23   121.2 2117.06   134.3 2106.49
   183.4 2074.72   248.9 2036.44   275.1  2025.1   317.7 2016.28   330.8  2010.7
   343.9 2002.32   360.3 2001.22   366.8 1997.58   386.4 1982.45   396.2  1979.1
   409.3 1977.36   419.1 1977.84   422.4 1979.48   428.9 1984.17   435.4 1985.36
   471.4 1984.86  485.431986.117  524.011986.642   553.1 1986.16   566.2 1990.58
   582.6    1993   595.6 1998.75   615.2 2001.58   638.1 2008.28     782 2089.33
#Mann= 5 ,-1 , 0
       0     .12       0   396.2    .045       0   422.4     .12       0
  485.43    .016       0  524.01     .12       0
Bank Sta=396.2,422.4
XS Rating Curve= 0 ,0
Exp/Cntr=0.3,0.1

Type RM Length L Ch R = 1 ,5986.9  ,282,264.1,245.4
XS GIS Cut Line= 3
     2175629.783      233747.809     2175898.888      233498.655
     2176168.816      233253.234
#Sta/Elev= 30
       0 2172.51    29.5 2151.96    75.3 2118.51   180.1 2038.98   206.3 2020.15
   225.9  2007.7     239  2000.9     262 1993.33   281.6 1984.35   288.2 1983.18
  323.711983.853     334 1983.09   353.6 1978.34   366.7 1974.79   376.5 1975.44
     383 1977.74     396 1981.61   412.3 1985.08     471 1991.66     484 1996.66
   529.6 2011.16   545.9 2014.97   607.8 2026.94   617.6 2027.65   627.3 2022.88
   633.8 2022.34   640.4 2024.41   679.4 2043.19   705.5  2050.1   731.6  2055.5
#Mann= 4 ,-1 , 0
       0     .12       0  323.71    .016       0   353.6    .045       0
     383     .12       0
Bank Sta=353.6,383
XS Rating Curve= 0 ,0
Exp/Cntr=0.3,0.1

Type RM Length L Ch R = 1 ,5722.8  ,190.4,179.8,168.1
XS GIS Cut Line= 3
     2175837.301      233937.081     2176079.556      233710.231
      2176225.17      233299.049
#Sta/Elev= 30
       0 2158.47    48.8 2126.02   133.4 2066.79   165.9 2046.14   188.7 2032.92
     218 2017.94   250.5 2004.43   270.1 2000.07   296.1 1997.22   302.6 1995.16
  307.821991.726   325.4 1980.58   328.6 1979.33     345 1978.92   351.21976.425
   351.6 1976.23   361.4 1974.65   384.4 1976.06     404 1979.72     427 1981.72
   456.5 1986.21   499.2 1990.18   541.8 1992.39   587.7 2002.05   613.9 2013.11
   646.7 2031.48   686.1 2054.94   735.3 2080.99   751.7 2087.62   768.1 2092.19
#Mann= 5 ,-1 , 0
       0     .12       0  307.82    .016       0   351.2     .12       0
   351.6    .045       0   384.4     .12       0
Bank Sta=351.6,384.4
XS Rating Curve= 0 ,0
Exp/Cntr=0.3,0.1

Type RM Length L Ch R = 1 ,5543.1  ,238.9,302.3,360.2
XS GIS Cut Line= 4
     2175880.135      233978.438      2176262.08      233839.549
     2176272.496      233605.174     2176481.181      233424.778
#Sta/Elev= 30
       0 2148.88    13.1 2139.16    49.2 2115.51   173.7 2025.34   219.6 1995.92
   242.5 1987.94   268.8 1984.22   304.8 1980.84   336.21981.042  377.31 1979.44
   406.4 1978.61   422.7 1975.15     452 1977.68   487.9 1977.98   536.8 1976.47
   559.6 1973.58   569.3 1972.58   579.1 1972.68   585.6 1973.94   595.4 1977.74
   618.2 1977.82   637.8 1982.14   660.5 1985.37   683.2 1993.76   709.2 2007.93
   731.9 2021.81   835.7 2095.96   897.4 2134.72   910.4 2145.13   916.9 2147.34
#Mann= 5 ,-1 , 0
       0     .12       0   336.2    .016       0  377.31     .12       0
   559.6    .045       0   585.6     .12       0
Bank Sta=559.6,585.6
XS Rating Curve= 0 ,0
Exp/Cntr=0.3,0.1

Type RM Length L Ch R = 1 ,5240.7  ,238,260.7,282.5
XS GIS Cut Line= 4
     2175896.123      234005.096     2176287.007      233867.894
     2176408.122      233865.784     2176648.801      233764.998
#Sta/Elev= 30
       0 2143.96    48.9    2111    91.3 2078.44   166.4  2023.5   208.8 1997.18
   231.6 1989.44   264.2 1983.99   303.4 1980.28  336.641979.764  377.841979.865
   420.8 1977.35   437.2 1971.16   443.7 1969.18   450.3 1969.08   466.6 1970.48
   496.1 1973.35   512.5 1973.55   522.3 1979.09   538.7 1992.13     555 2000.38
   597.4 2011.68   626.7 2023.09   708.3 2062.62   721.3 2070.66   724.6 2071.88
   734.4  2072.5   737.6 2074.02   744.1 2079.84   747.4 2081.68   796.3 2105.18
#Mann= 5 ,-1 , 0
       0     .12       0  336.64    .016       0  377.84     .12       0
   437.2    .045       0   466.6     .12       0
Bank Sta=437.2,466.6
XS Rating Curve= 0 ,0
Exp/Cntr=0.3,0.1