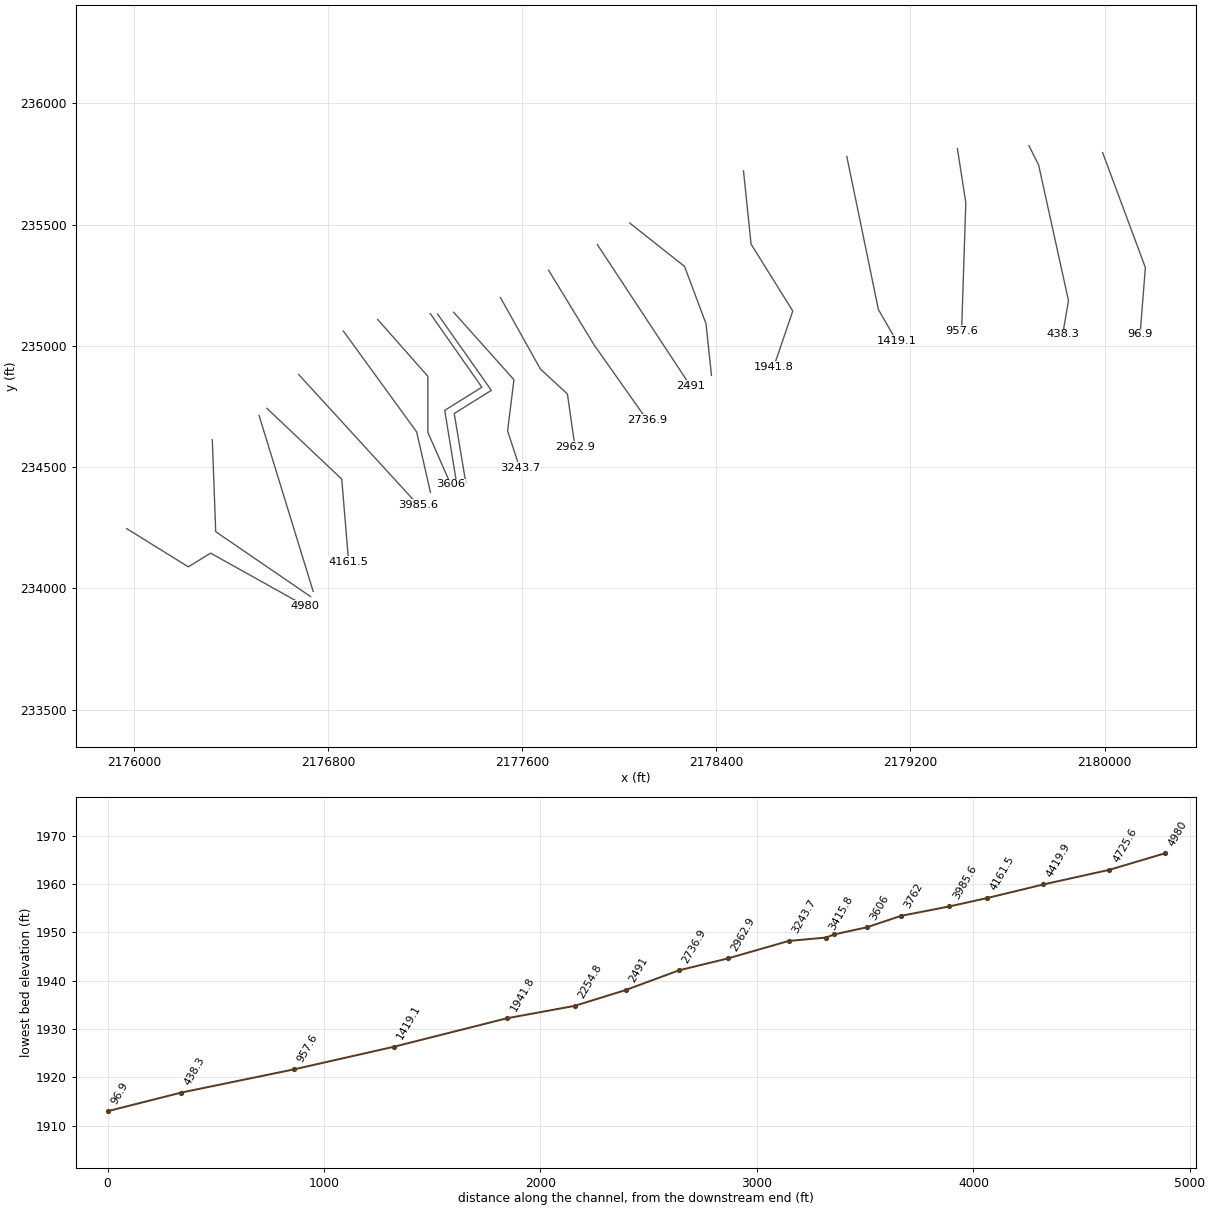
HEC-RAS study BACKCK2.prj: BACKCK2

--- BACKCK2.g01 (geometry) --- (continued)

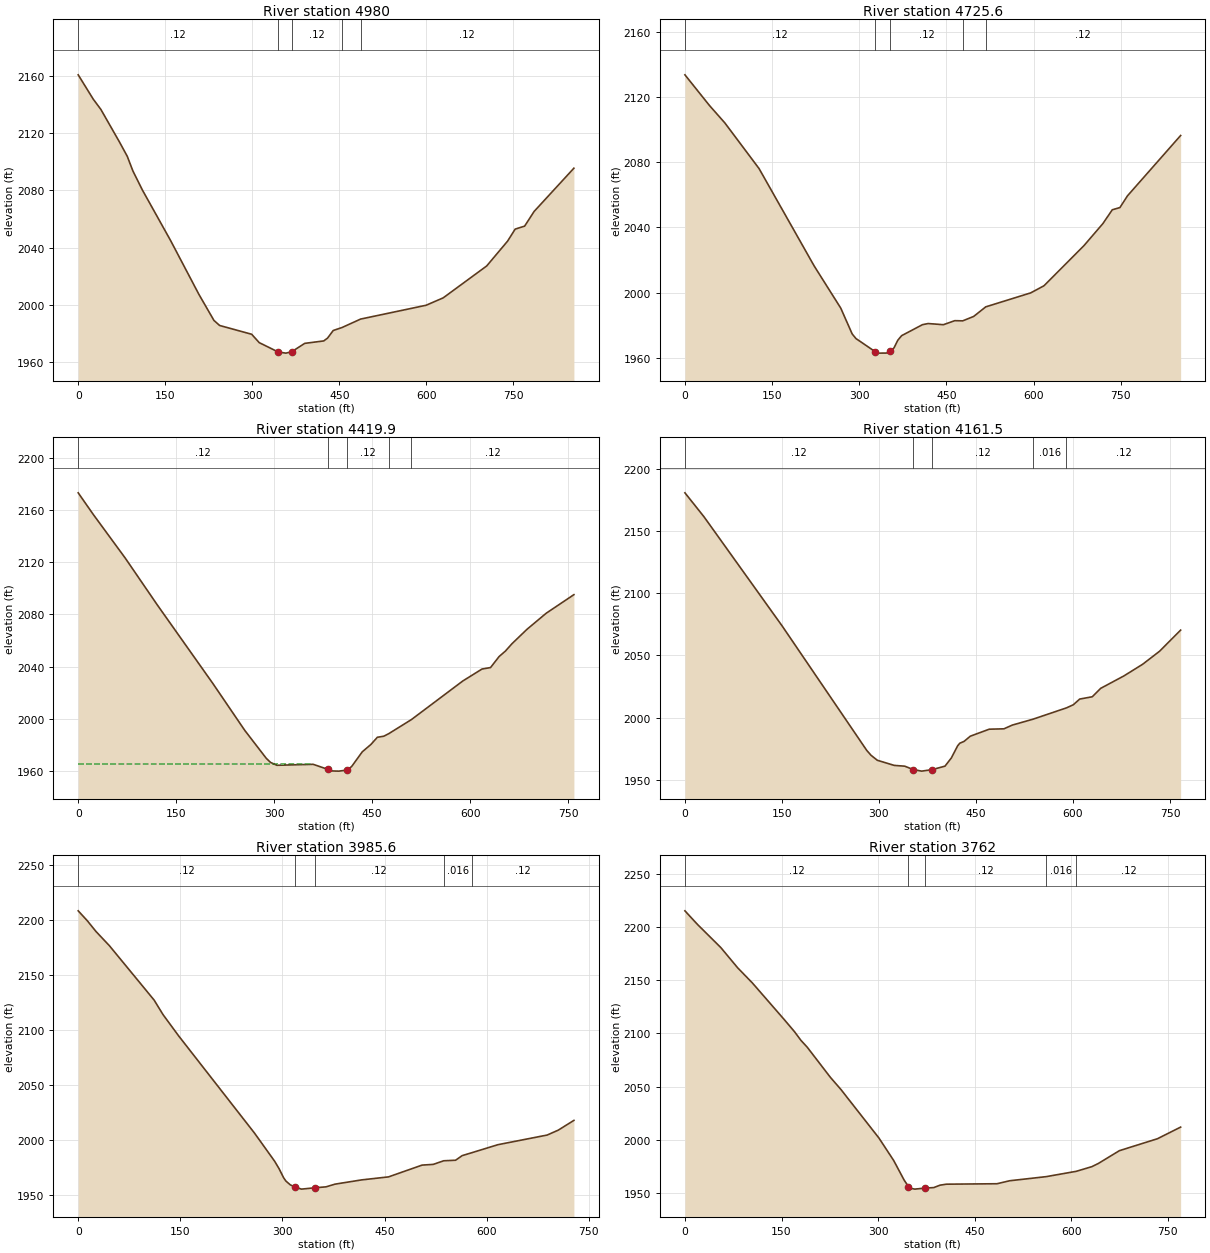
Type RM Length L Ch R = 1 ,4980    ,333.5,254.5,174.5
XS GIS Cut Line= 4
     2175970.022      234246.284     2176223.942      234088.622
     2176315.899      234145.105     2176706.508      233926.968
#Sta/Elev= 30
       0 2160.77      26 2143.73      39 2136.64    71.5 2113.57    84.5 2103.89
    94.2 2093.67   110.5 2080.38   159.2 2045.01   207.9 2007.47   233.9  1989.2
   243.7 1985.66   298.9 1979.52     312 1973.66   344.7 1967.13   357.8 1966.34
   367.6 1967.24   390.4 1973.16   423.1 1974.86   429.7 1976.83   439.5 1982.16
  454.581984.219  486.641990.125   599.5 1999.78   628.9 2004.93     704 2027.26
   739.9 2044.57     753 2052.99   769.3 2055.06   785.6  2065.3   854.2 2095.54
#Mann= 5 ,-1 , 0
       0     .12       0   344.7    .045       0   367.6     .12       0
  454.58    .016       0  486.64     .12       0
Bank Sta=344.7,367.6
XS Rating Curve= 0 ,0
Exp/Cntr=0.3,0.1

Type RM Length L Ch R = 1 ,4725.6  ,295.7,305.7,315.3
XS GIS Cut Line= 3
     2176322.769      234612.811     2176336.733      234233.647
     2176727.565      233966.048
#Sta/Elev= 30
       0  2133.5    42.5 2114.59    68.7 2104.03   127.6 2076.04   222.4 2016.39
   268.2 1990.52   287.8 1974.73   294.4 1971.87   327.1 1963.92   333.6 1962.95
   346.7 1962.98   353.2 1964.08   359.8 1966.14   366.3 1970.81   372.9 1973.64
   408.8 1980.39   418.6 1981.08   444.8 1980.37   464.4 1982.84  478.091982.726
     497 1985.45  517.761991.314     595 1999.86   617.9 2004.22   686.5 2028.74
   719.2 2042.28   735.5  2050.8   748.6 2052.15   761.6 2059.33   853.1 2096.32
#Mann= 5 ,-1 , 0
       0     .12       0   327.1    .045       0   353.2     .12       0
  478.09    .016       0  517.76     .12       0
Bank Sta=327.1,353.2
XS Rating Curve= 0 ,0
Exp/Cntr=0.3,0.1

Type RM Length L Ch R = 1 ,4419.9  ,239.4,258.5,277.2
XS GIS Cut Line= 2
     2176515.552      234712.813      2176738.42      233987.385
#Sta/Elev= 30
       0 2173.07    22.9 2156.63      72  2123.1     121 2087.29   206.1 2027.09
   255.1 1991.06   287.9 1969.75   294.4  1966.6   304.2 1964.38   359.8 1965.12
   382.7 1961.19   389.3 1960.04   399.1 1959.91   412.2 1960.77   418.7 1963.49
     435 1974.75   448.1 1980.32     458 1985.84   467.8 1986.64  475.321988.568
  510.081999.361   588.8 2028.95   618.2  2038.1   631.3 2039.24   644.4 2047.68
   654.2 2051.93     664 2057.45   686.9 2068.45   716.4 2080.81   758.9 2095.07
#Mann= 5 ,-1 , 0
       0     .12       0   382.7    .045       0   412.2     .12       0
  475.32    .016       0  510.08     .12       0
#XS Ineff= 2 , 0
          359.86 1965.14
Permanent Ineff=
       F       F
Bank Sta=382.7,412.2
XS Rating Curve= 0 ,0
Exp/Cntr=0.3,0.1

Type RM Length L Ch R = 1 ,4161.5  ,177.8,175.9,175.8
XS GIS Cut Line= 3
     2176547.565      234742.507     2176856.252      234450.416
     2176884.466      234110.196
#Sta/Elev= 30
       0 2180.57    29.4  2161.4   150.4 2073.61   281.1 1973.77   287.7 1969.85
   297.5 1965.82   323.6 1961.72     340 1961.07   353.1 1958.32   366.1 1957.11
   382.5 1958.33   402.1 1961.12   411.9 1967.68   421.7 1977.48     425 1979.54
   431.5 1980.95   441.2 1985.16   470.5 1990.78   493.2 1991.08   506.3  1994.1
  538.221998.819  589.842007.885   600.6 2010.43   610.3 2014.96   629.8 2016.82
   642.8 2023.58   678.6 2033.52   707.8 2042.96   733.8 2053.35   766.4 2070.34
#Mann= 5 ,-1 , 0
       0     .12       0   353.1    .045       0   382.5     .12       0
  538.22    .016       0  589.84     .12       0
Bank Sta=353.1,382.5
XS Rating Curve= 0 ,0
Exp/Cntr=0.3,0.1

Type RM Length L Ch R = 1 ,3985.6  ,227.4,223.5,216.9
XS GIS Cut Line= 2
     2176678.674      234881.914     2177170.066      234344.758
#Sta/Elev= 30
       0 2208.54    13.1 2199.72    26.2  2189.7    45.9 2176.76   111.5 2127.34
   124.6 2114.11   147.6 2094.71   259.1  2006.2   288.6 1980.64   295.1 1973.85
   301.7 1965.71     305 1962.74   311.5 1959.24   318.7 1957.21   327.9 1955.36
   347.6  1956.6     364 1957.44   377.1 1959.88   416.5 1963.78   455.8  1966.5
     505 1977.21   521.4 1977.86  536.821981.148   554.2 1981.64     564 1985.86
  578.591988.579   616.5  1995.8   688.7 2004.55   705.1 2009.04     728  2017.9
#Mann= 5 ,-1 , 0
       0     .12       0   318.7    .045       0   347.6     .12       0
  536.82    .016       0  578.59     .12       0
Bank Sta=318.7,347.6
XS Rating Curve= 0 ,0
Exp/Cntr=0.3,0.1

Type RM Length L Ch R = 1 ,3762    ,177.9,156,130.3
XS GIS Cut Line= 3
     2176862.891      235061.152     2177164.858      234645.105
     2177221.858      234395.805
#Sta/Elev= 30
       0 2215.42    19.6 2202.55    55.7 2180.85    81.9 2161.78   104.8 2147.48
   153.9 2113.27   170.3 2101.54   180.1 2093.52   189.9 2087.06   225.9 2058.65
   242.3 2047.19   301.2  2001.6   324.2 1980.36   340.5 1961.83   347.1 1955.86
   350.4 1954.24   356.9 1953.41   373.3 1954.42   386.4 1954.86   396.2 1957.13
     406 1958.06   484.6 1958.48   504.3 1961.29  561.021965.161   607.81970.185
   632.1  1974.6     642 1977.56   674.7 1989.61   733.8 2000.85   769.8  2011.8
#Mann= 5 ,-1 , 0
       0     .12       0   347.1    .045       0   373.3     .12       0
  561.02    .016       0   607.8     .12       0
Bank Sta=347.1,373.3
XS Rating Curve= 0 ,0
Exp/Cntr=0.3,0.1

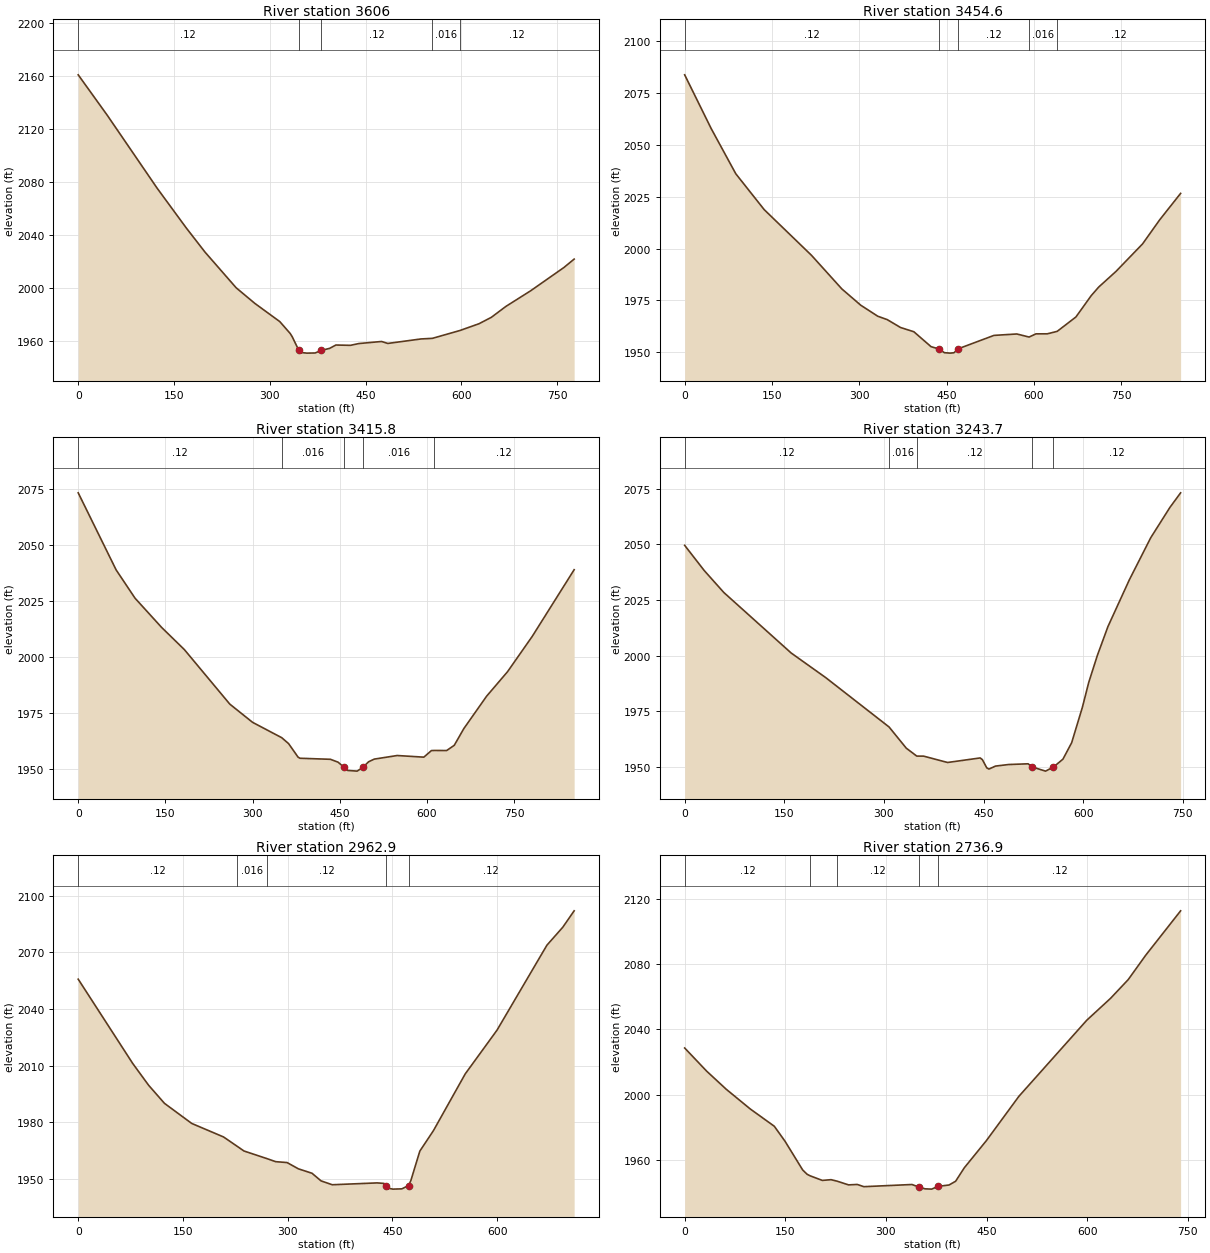
Type RM Length L Ch R = 1 ,3606    ,193.3,151.4,110.9
XS GIS Cut Line= 4
     2177004.412      235108.791     2177211.009      234874.416
     2177211.009      234643.514     2177304.759      234429.972
#Sta/Elev= 30
       0  2160.9    45.6 2130.34   123.7 2075.35   169.2 2045.45   198.5 2027.27
   247.3 2000.34   276.6 1988.55   315.7 1974.82     332 1965.84   335.2 1963.35
     345 1953.57   348.2 1951.56     358 1951.06     371 1951.17   380.7 1953.13
   393.7 1954.65   403.5 1957.17   426.3 1956.93   439.3 1958.27     475 1959.84
   484.8 1958.36   536.8 1961.75  554.491962.188  597.761968.122   627.6 1973.22
     647 1978.07   669.7 1986.27   708.5 1998.07   760.4 2015.56   776.6 2021.96
#Mann= 5 ,-1 , 0
       0     .12       0     345    .045       0   380.7     .12       0
  554.49    .016       0  597.76     .12       0
Bank Sta=345,380.7
XS Rating Curve= 0 ,0
Exp/Cntr=0.3,0.1

Type RM Length L Ch R = 1 ,3454.6  ,37.5,38.8,37.5
XS GIS Cut Line= 4
     2177220.992      235133.314     2177433.665      234829.494
     2177280.671      234734.008     2177329.065      234436.916
#Sta/Elev= 30
       0  2083.9    45.5 2057.99    87.8 2036.16   136.6 2018.85     218 1996.76
     270 1980.59   302.5 1972.72   331.8 1967.39   348.1 1965.75   370.9 1961.95
   393.8  1959.9   423.3 1952.71   436.4 1951.62   446.3 1949.79   456.1 1949.58
   462.7 1949.75   470.1 1951.68   531.5 1958.14   570.8 1958.82  591.831957.342
   603.6 1958.88   623.2  1958.9   640.11960.086   672.3 1967.03   698.4 1977.26
   711.5 1981.48     741 1988.98   786.8 2002.29   816.2  2013.9   852.2 2026.68
#Mann= 5 ,-1 , 0
       0     .12       0   436.4    .045       0   470.1     .12       0
  591.83    .016       0   640.1     .12       0
Bank Sta=436.4,470.1
XS Rating Curve= 0 ,0
Exp/Cntr=0.3,0.1

Type RM Length L Ch R = 1 ,3415.8  ,136.7,172.2,208.9
XS GIS Cut Line= 4
     2177251.374      235131.144     2177472.728      234816.474
     2177319.733      234720.988     2177367.259      234436.916
#Sta/Elev= 30
       0 2073.22    65.2 2038.81    97.8 2026.15   143.5  2013.1   182.6  2003.2
   260.8 1978.84     300  1970.7  350.17 1963.84   361.9 1961.21   378.2 1955.17
   381.5 1954.67   433.9  1954.2     447 1952.92   456.9 1950.71   463.4 1949.23
   479.8 1948.92   489.7 1950.59   499.5  1953.1   509.3 1954.29   548.7 1955.89
   594.5 1955.16   607.6  1958.1  612.791958.144   633.8 1958.12   646.9 1960.46
   663.3  1967.9   702.5 1982.38   738.5 1993.32   781.1 2009.14   853.1 2038.88
#Mann= 5 ,-1 , 0
       0     .12       0  350.17    .016       0   456.9    .045       0
   489.7    .016       0  612.79     .12       0
Bank Sta=456.9,489.7
XS Rating Curve= 0 ,0
Exp/Cntr=0.3,0.1

Type RM Length L Ch R = 1 ,3243.7  ,244.1,280.8,316.5
XS GIS Cut Line= 4
     2177317.505      235138.551     2177565.899      234860.383
     2177539.727      234648.968     2177590.075       234496.19
#Sta/Elev= 30
       0 2049.57    29.4 2038.28    58.9 2028.42   160.3 2001.26   212.6 1990.15
  307.741968.048   333.7 1958.52  349.491954.967   359.8 1954.95   395.9  1952.1
     445 1954.14   448.3 1953.37   454.9 1949.69   458.1 1949.14     468 1950.48
   487.6 1951.18   517.1 1951.51   523.7 1950.05   543.4 1948.22   555.2 1950.03
   569.6 1953.59   582.7 1960.95   598.8 1976.79   608.5  1988.1   621.4 2000.13
   637.4 2013.13   669.6  2034.1   701.8 2052.99   730.7 2066.61   746.8 2073.15
#Mann= 5 ,-1 , 0
       0     .12       0  307.74    .016       0  349.49     .12       0
   523.7    .045       0   555.2     .12       0
#XS Ineff= 2 , 0
          444.76 1954.12
Permanent Ineff=
       F       F
Bank Sta=523.7,555.2
XS Rating Curve= 0 ,0
Exp/Cntr=0.3,0.1

Type RM Length L Ch R = 1 ,2962.9  ,236.2,226,217.8
XS GIS Cut Line= 4
     2177510.213      235199.315     2177675.144      234904.176
     2177786.255      234801.746     2177817.505      234582.996
#Sta/Elev= 30
       0 2055.85      78 2011.23   100.8 1999.66   123.5 1990.07   162.6  1979.4
   208.1 1972.25  227.961967.212   237.3 1964.82  270.891960.691   282.8 1959.15
   299.1 1958.68   315.3 1955.36   334.8 1953.01   347.7 1948.98   363.8 1946.92
   428.1  1947.9   437.8 1947.63     441 1946.51   444.2 1945.08   450.6  1944.6
   463.5 1944.75   473.1 1946.49   476.4 1949.19   489.2 1964.73   508.7  1975.6
   554.2 2005.65   599.7 2028.82   671.2 2073.87   693.9 2083.37   710.2 2092.08
#Mann= 5 ,-1 , 0
       0     .12       0  227.96    .016       0  270.89     .12       0
     441    .045       0   473.1     .12       0
Bank Sta=441,473.1
XS Rating Curve= 0 ,0
Exp/Cntr=0.3,0.1

Type RM Length L Ch R = 1 ,2736.9  ,244.5,245.9,244.6
XS GIS Cut Line= 3
     2177708.634      235312.267     2177896.637       235003.41
     2178114.323      234694.713
#Sta/Elev= 30
       0 2028.61    32.6  2014.5    61.9 2003.35    97.7 1991.28   133.6 1980.66
   149.8 1971.35   175.9 1953.89   182.4 1951.28  187.161950.268   205.2 1947.48
   218.2 1947.93  227.081947.037   244.3 1944.74   257.3    1945   267.1 1943.64
   338.8 1944.97   348.6 1943.51   358.3 1942.32   368.1 1942.14   377.9 1943.83
   394.1 1944.67   403.9 1946.97   416.9 1955.24   449.5 1971.72   498.3 1999.04
   599.3 2045.58   635.1 2059.14   661.2 2070.52   687.2 2085.41   739.3 2112.66
#Mann= 5 ,-1 , 0
       0     .12       0  187.16    .016       0  227.08     .12       0
   348.6    .045       0   377.9     .12       0
Bank Sta=348.6,377.9
XS Rating Curve= 0 ,0
Exp/Cntr=0.3,0.1

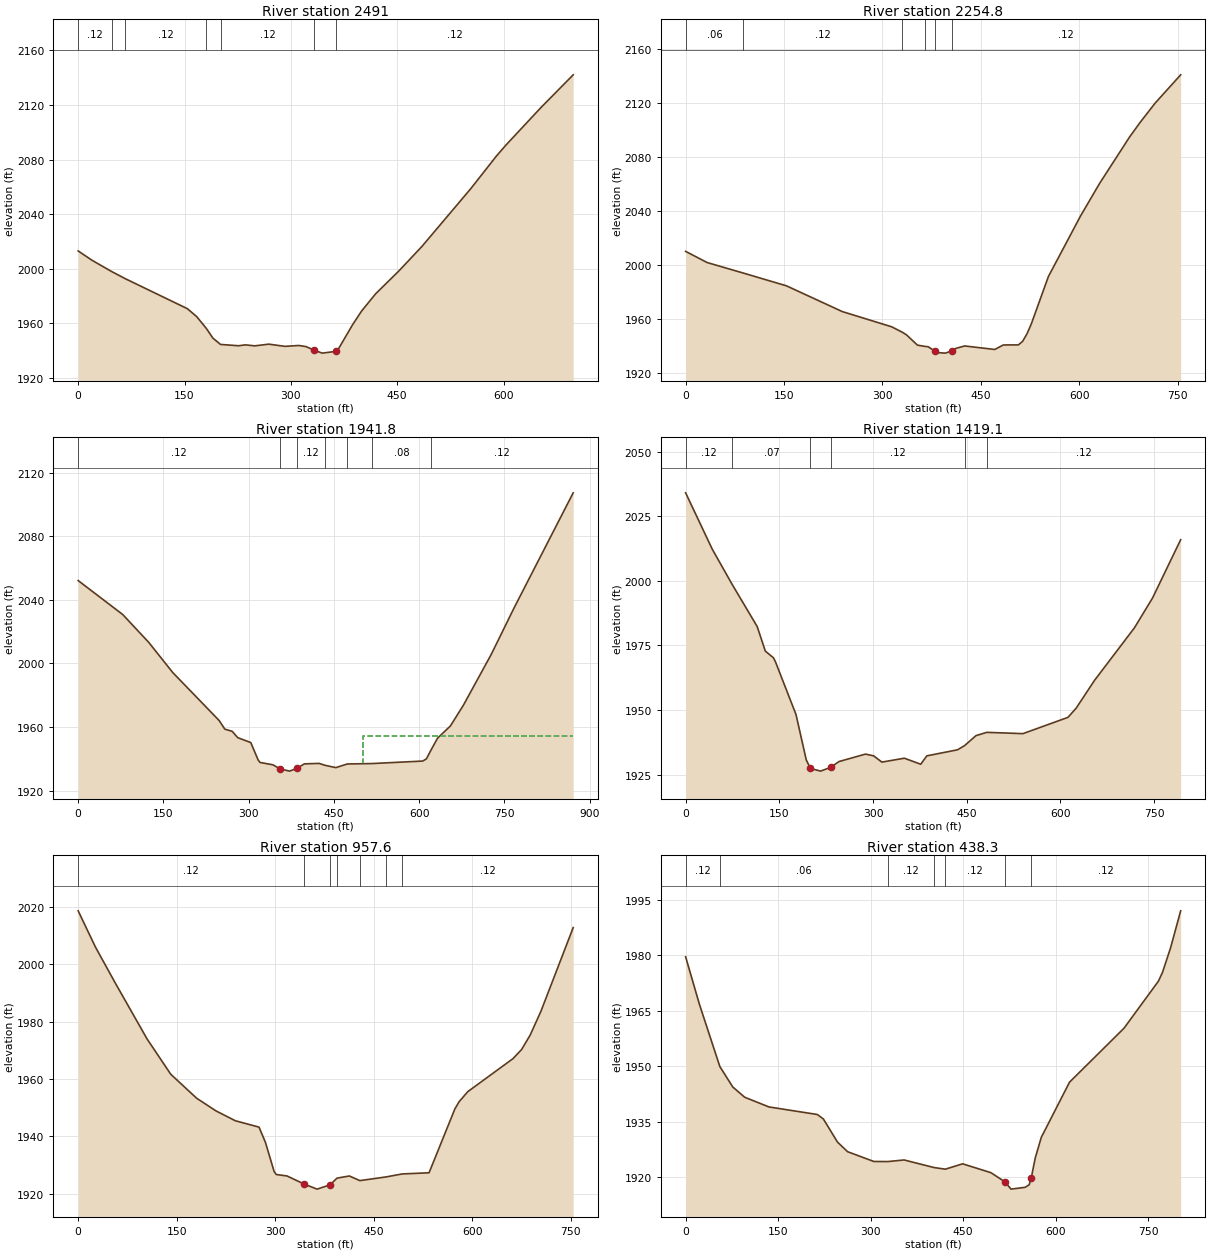
Type RM Length L Ch R = 1 ,2491    ,244.5,236.2,227.5
XS GIS Cut Line= 2
     2177909.519      235418.065       2178293.2      234834.732
#Sta/Elev= 30
       0    2013    19.7  2006.1   47.441997.843   66.471992.647   154.1 1970.63
   167.2 1964.82  180.711956.224   190.1 1949.03  200.861944.426   226.2 1943.47
     236 1944.12   249.1 1943.39   268.8 1944.64   291.7 1943.03   311.4 1943.66
   321.2 1942.86   333.1 1940.18   344.2 1938.06   363.8 1939.36   367.1 1941.16
   386.8 1958.68   399.9 1969.04   419.6 1981.59   452.4 1998.35   485.1 2016.45
     554 2058.84     590 2082.65   603.1 2090.49   652.3 2117.94   698.2 2142.15
#Mann= 7 ,-1 , 0
       0     .12       0   47.44     .06       0   66.47     .12       0
  180.71    .016       0  200.86     .12       0   333.1    .045       0
   363.8     .12       0
Bank Sta=333.1,363.8
XS Rating Curve= 0 ,0
Exp/Cntr=0.3,0.1

Type RM Length L Ch R = 1 ,2254.8  ,305.3,313,320.1
XS GIS Cut Line= 4
       2178043.2      235506.607     2178268.894      235327.787
     2178357.436      235091.676     2178380.005      234878.135
#Sta/Elev= 30
       0 2010.18    32.7 2001.91   87.95  1994.1   153.8 1984.63   238.9 1965.56
   314.2 1954.28  330.651950.189   337.1 1948.19   353.4 1940.73  364.671939.769
   369.8 1939.52   379.6 1936.39   386.2 1935.08     396 1934.78   405.8 1936.42
   412.4 1938.36   425.5 1940.09   471.3 1937.49   484.4 1940.83   507.4 1940.88
   513.9 1943.56   520.5  1949.1     527 1956.32   553.1 1991.49   601.9  2036.2
   631.2 2060.53   676.8 2094.82     693 2105.72   715.8 2119.96   754.8 2140.97
#Mann= 6 ,-1 , 0
       0     .06       0   87.95     .12       0  330.65    .016       0
  364.67     .12       0   379.6    .045       0   405.8     .12       0
Bank Sta=379.6,405.8
XS Rating Curve= 0 ,0
Exp/Cntr=0.3,0.1

Type RM Length L Ch R = 1 ,1941.8  ,536,522.7,508.9
XS GIS Cut Line= 4
      2178511.95      235721.885       2178543.2      235419.801
     2178715.075       235143.76      2178636.95      234914.593
#Sta/Elev= 30
       0 2052.05    78.4  2030.7   124.1 2013.22   166.5 1994.18   248.2 1963.99
     258 1958.61     271 1957.24   280.8 1953.25   303.7 1950.18   316.7 1939.18
     320 1937.68   342.7 1936.18   355.7 1933.56     372 1932.21     385 1934.01
     398 1936.77     424 1937.07  434.671935.844   453.3 1934.42  473.561936.706
  516.961936.962   606.1 1938.54   612.6 1939.88   620.61945.292   632.1 1952.82
     655 1960.65     678 1973.78     727 2005.76   766.3 2034.37     871 2107.23
#Mann= 7 ,-1 , 0
       0     .12       0   355.7    .045       0     385     .12       0
  434.67     .06       0  473.56    .016       0  516.96     .08       0
   620.6     .12       0
#XS Ineff= 2 , 0
                          500.63         1954.21
Permanent Ineff=
       F       F
Bank Sta=355.7,385
XS Rating Curve= 0 ,0
Exp/Cntr=0.3,0.1

Type RM Length L Ch R = 1 ,1419.1  ,471,461.5,449.2
XS GIS Cut Line= 3
     2178937.731      235781.346     2179067.939      235149.836
     2179141.724      235021.798
#Sta/Elev= 30
       0 2034.01    42.6 2012.22   74.781998.458   114.6 1982.26   127.6 1972.76
   140.7 1970.15     144 1968.52   176.8 1948.17   193.1 1930.69   199.7 1927.39
     216 1926.31   232.4 1927.78   245.5 1930.01     288  1932.9   301.1 1932.22
   314.2  1929.8   350.2 1931.31   376.4 1928.98   386.2 1932.22   435.3 1934.56
  446.731936.196   464.8 1940.03  482.121941.315   540.1 1940.82   612.1 1947.11
   625.2 1950.64   654.4 1961.34   718.7 1981.81   747.6 1993.32   792.6 2015.86
#Mann= 6 ,-1 , 0
       0     .12       0   74.78     .07       0   199.7    .045       0
   232.4     .12       0  446.73    .016       0  482.12     .12       0
Bank Sta=199.7,232.4
XS Rating Curve= 0 ,0
Exp/Cntr=0.3,0.1

Type RM Length L Ch R = 1 ,957.6   ,506.9,519.3,530.2
XS GIS Cut Line= 3
      2179393.46      235813.898     2179428.182      235590.374
     2179410.821       235063.03
#Sta/Elev= 30
       0 2018.58    26.2 2006.01    55.7 1993.76   104.9 1973.96     141 1961.65
   180.3 1953.32   209.8 1948.89   239.3 1945.45   275.4 1943.23   285.2  1937.9
   298.3 1927.83   301.6 1926.72     318 1926.22   344.2 1923.39   363.8 1921.63
   383.5 1923.12  394.211925.463     413 1926.21  428.921924.592  469.381925.901
  493.46 1926.92   534.3 1927.32   573.6 1949.55   580.1 1952.09   593.2 1955.57
   662.1 1967.09   675.2 1970.25   688.3  1975.3   704.7 1983.61   753.8 2012.74
#Mann= 7 ,-1 , 0
       0     .12       0   344.2    .045       0   383.5     .12       0
  394.21    .016       0  428.92     .12       0  469.38     .08       0
  493.46     .12       0
Bank Sta=344.2,383.5
XS Rating Curve= 0 ,0
Exp/Cntr=0.3,0.1

Type RM Length L Ch R = 1 ,438.3   ,335.8,341.4,347
XS GIS Cut Line= 4
      2179688.44      235825.805      2179728.37      235745.944
     2179851.359      235186.728     2179827.488      235047.839
#Sta/Elev= 30
       0 1979.54    22.3 1966.76    55.51949.917    76.5  1944.4    95.8 1941.64
   135.1 1939.02   213.6 1936.98   223.4 1935.77   246.3 1929.53   262.7 1926.94
   305.2  1924.3  328.011924.279   354.3 1924.71     4031922.658  421.191922.228
   449.2 1923.67     495 1921.29   517.9  1918.8   527.7 1916.84   550.6 1917.33
   557.2 1918.04   560.4 1919.79     567 1925.26   576.8 1930.82   622.6 1945.71
     711 1960.28   766.7 1972.96   773.3 1975.32   786.4 1981.94   802.8 1991.95
#Mann= 7 ,-1 , 0
       0     .12       0    55.5     .06       0  328.01     .12       0
     403    .016       0  421.19     .12       0   517.9    .045       0
   560.4     .12       0
Bank Sta=517.9,560.4
XS Rating Curve= 0 ,0
Exp/Cntr=0.3,0.1

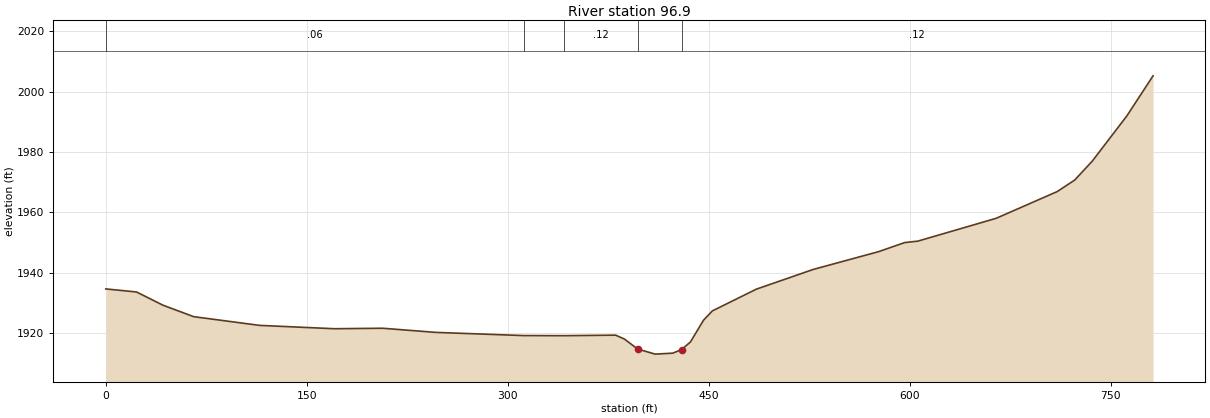
Type RM Length L Ch R = 1 ,96.9    ,107.9,96.9,85.5
XS GIS Cut Line= 3
     2179992.114      235797.015       2180168.2      235323.447
     2180146.498      235047.839
#Sta/Elev= 30
       0 1934.59      23 1933.57    42.6 1929.21    65.6 1925.39   114.8  1922.5
   170.6 1921.39   206.7 1921.55   246.1 1920.18  311.84 1919.12  341.861919.084
   380.6 1919.26   387.1 1917.97     397 1914.66   410.1 1912.97   423.2 1913.29
   429.8 1914.48   436.4 1917.01   446.2 1924.24   452.8 1927.31   485.6 1934.51
     528 1941.04   576.8 1946.94   596.3 1949.95   606.1 1950.43   664.6    1958
   710.2 1966.87   723.2 1970.68   736.2 1976.88   762.2 1991.98   781.7 2005.24
#Mann= 5 ,-1 , 0
       0     .06       0  311.84    .016       0  341.86     .12       0
     397    .045       0   429.8     .12       0
Bank Sta=397,429.8
XS Rating Curve= 0 ,0
Exp/Cntr=0.3,0.1

Chan Stop Cuts=-1
Use User Specified Reach Order=0
Composite Channel Slope=5